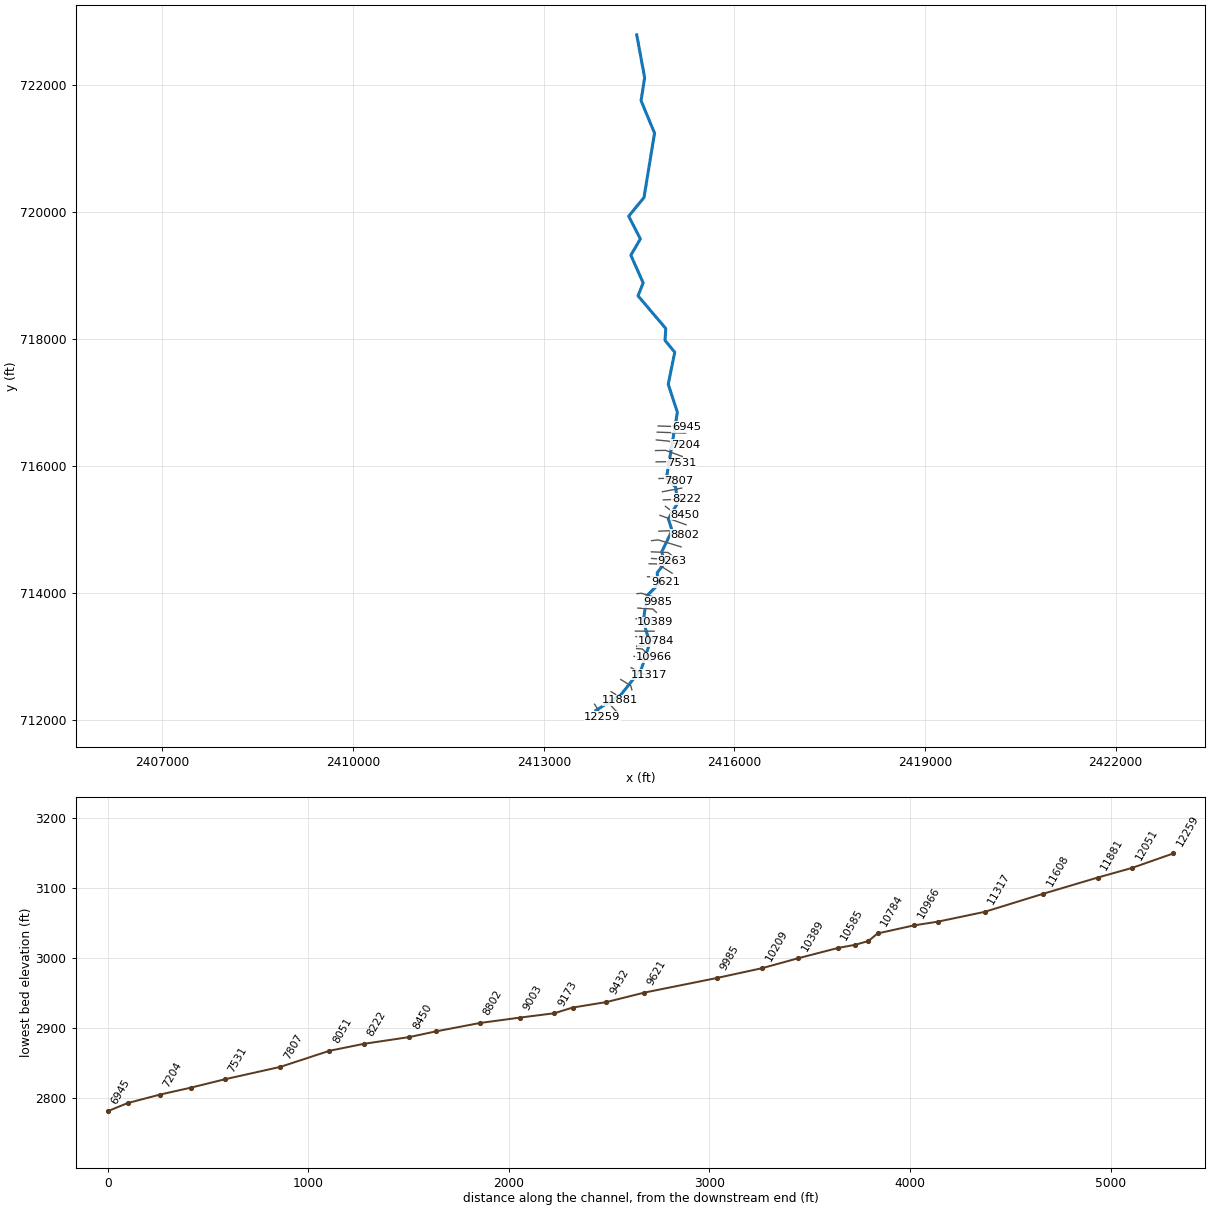
--- FLATROCKRN.prj (project) ---

Proj Title=FLATROCKRN
Current Plan=p01
Default Exp/Contr=0,0
English Units
Geom File=g01
Flow File=f01
Plan File=p01
BEGIN DESCRIPTION:
----------MODEL BY WOOD PLC 2022----------
AFH study
Randolph County, WV
HEC-RAS Version: RAS 6.2
Vertical Datum: NAVD88
Projection: NAD 1983 StatePlane West Virginia S FIPS 4702 (US Feet)
Terrain: 1-meter LIDAR (FEMA Region III 3DEP collected 2016-2018)
Land Use: 2019 NLCD
Hydrologic Method:
WV SIR2010-5033 regression equations
Additional Model Notes:
None
END DESCRIPTION:
DSS Export Rating Curves= 0
DSS Export Rating Curve Sorted= 0
DSS Export Volume Flow Curves= 0
DXF OffsetX= 0
DXF OffsetY= 0
DXF ScaleX= 0
DXF ScaleY= 0

--- FLATROCKRN.p01 (plan) ---

Plan Title=Floodplain
Program Version=6.20
Short Identifier=Floodplain
Geom File=g01
Flow File=f01
Subcritical Flow
K Sum by GR= 0
Std Step Tol= 0.01
Critical Tol= 0.01
Num of Std Step Trials= 20
Max Error Tol= 0.3
Flow Tol Ratio= 0.001
Split Flow NTrial= 30
Split Flow Tol= 0.02
Split Flow Ratio= 0.02
Log Output Level= 0
Friction Slope Method= 1
Unsteady Friction Slope Method= 2
Unsteady Bridges Friction Slope Method= 1
Parabolic Critical Depth
Global Vel Dist= 0 , 0 , 0
Global Log Level= 0
CheckData=True
Encroach Param=-1 ,0,0, 0
Mapping Interval=1HOUR
Computation Time Step Use Courant=        0
Computation Time Step Use Time Series=    0
Computation Time Step Count To Double=0
Computation Time Step Max Doubling=0
Computation Time Step Max Halving=0
Computation Time Step Residence Courant=0
Run HTab= 0
Run UNet= 0
Run Sediment= 0
Run PostProcess= 0
Run WQNet= 0
Run RASMapper=-1
UNET Theta= 0
UNET Theta Warmup= 0
UNET ZTol= 0
UNET ZSATol= 0
UNET MxIter= 0
UNET Max Iter WO Improvement= 0
UNET MaxInSteps= 0
UNET DtIC= 0
UNET DtMin= 0
UNET MaxCRTS= 0
UNET WFStab= 0
UNET SFStab= 0
UNET WFX= 1
UNET SFX= 1
UNET Gravity=32.174
UNET 1D Methodology=Finite Difference
UNET DSS MLevel= 1
UNET Pardiso=0
UNET DZMax Abort= 0
UNET Use Existing IB Tables= 0
UNET Froude Reduction=False
UNET Froude Limit= 0
UNET Froude Power= 0
UNET D1 Cores= 0
UNET WindReference=Eulerian
UNET WindDragFormulation=Hsu (1988)
UNET D2 Coriolis=0
UNET D2 Cores= 0
UNET D2 Theta= 1
UNET D2 Theta Warmup= 1
UNET D2 Z Tol= 0.01
UNET D2 Volume Tol= 0.01
UNET D2 Max Iterations= 20
UNET D2 Equation= 0
UNET D2 RampUpFraction=0.1
UNET D2 TimeSlices= 1
UNET D2 Turbulence Formulation=Non-Conservative (original)
UNET D2 Eddy Viscosity=0.3
UNET D2 Transverse Eddy Viscosity=0.1
UNET D2 Smagorinsky Mixing=0
UNET D2 BCVolumeCheck=0
UNET D2 Cores=0
UNET D2 SolverType=PARDISO (Direct)
UNET D2 Minimum Iterations= 2147483647
UNET D2 Maximum Iterations= 2147483647
UNET D2 Restart Number= 10
UNET D2 Relaxation Coeff=1.3
UNET D2 SOR Precondition Iterations= 10
UNET D2 ILUT Maximum Fill= 8
UNET D2 ILUT Tolerance=1E-08
UNET D1D2 MaxIter= 0
UNET D1D2 ZTol=0.01
UNET D1D2 QTol=0.1
UNET D1D2 MinQTol=1
Write IC File= 0
Write IC File at Fixed DateTime=0
Write IC File at Sim End=0
Echo Input=False
Echo Parameters=False
Echo Output=False
Write Detailed= 0
HDF Write Warmup=0
HDF Write Time Slices=0
HDF Flush=0
HDF Compression= 1
HDF Chunk Size= 1
HDF Spatial Parts= 1
HDF Use Max Rows=0
HDF Fixed Rows= 1
Calibration Method= 0
Calibration Iterations= 20
Calibration Max Change=0.05
Calibration Tolerance=0.2
Calibration Maximum=1.5
Calibration Minimum=0.5
Calibration Optimization Method= 1
WQ AD Non Conservative
WQ ULTIMATE=-1
WQ Max Comp Step=1HOUR
WQ Output Interval=15MIN
WQ Output Selected Increments= 0
WQ Output face flow=0
WQ Output face velocity=0
WQ Output face area=0
WQ Output face dispersion=0
WQ Output cell volume=0
WQ Output cell surface area=0
WQ Output cell continuity=0
WQ Output cumulative cell continuity=0
WQ Output face conc=0
WQ Output face dconc_dx=0
WQ Output face courant=0
WQ Output face peclet=0
WQ Output face adv mass=0
WQ Output face disp mass=0
WQ Output cell mass=0
WQ Output cell source sink temp=0
WQ Output nsm pathways=0
WQ Output nsm derived pathways=0
WQ Create Restart=0
WQ Fixed Restart=0
WQ System Summary=0
WQ Write To DSS=0
Sorting and Armoring Iterations= 10
XS Update Threshold= 0.02
Bed Roughness Predictor= 0
Hydraulics Update Threshold= 0.02
Energy Slope Method= 1
Volume Change Method= 1
Sediment Retention Method= 0
Sediment TS Multiplier= 1
Warm Up Method= 0
XS Weighting Method= 0
Number of US Weighted Cross Sections= 1
Number of DS Weighted Cross Sections= 1
Upstream XS Weight=0
Main XS Weight=1
Downstream XS Weight=0
Number of DS XS's Weighted with US Boundary= 1
Upstream Boundary Weight= 1
Weight of XSs Associated with US Boundary= 0
Number of US XS's Weighted with DS Boundary= 1
Downstream Boundary Weight= 0.5
Weight of XSs Associated with DS Boundary= 0.5
Percentile Method= 0
Sediment Output Level= 3
Mass or Volume Output= 0
Output Increment Type= 1
Profile and TS Output Increment= 1
Transport Output Increment 1
XS Output Flag= 0
XS Output Increment= 10
Read HDF5 Sediment Hotstart= 0
Sediment Hotstart Type= 0
Write Gradation File= 0
Read Gradation Hotstart= 0
Write HDF5 File= 1
Write Binary Output= 1
Write DSS Sediment File= 0
DSS Sediment Output Type= 1
SV Curve= 0
Specific Gage Flag= 0
Subcell Erosion Methods= 0
Subcell Deposition Methods= 0
Advection Scheme= 1
Matrix Solver= 0
Implicit Weighting Factor= 1
Maximum Outer Loop Convergence Iterations= 5
Convergence Maximum Absolute= 0.001
Convergence RMSE= 0.0001
Grain Fractions Max Abs Error= 0.001
Max Subgrid Regions= 1
Max Subgrid Length Scale= 3.402823E+38
Initial Layer Thickness= 3.402823E+38
Min Layer Thickness= 3.402823E+38
Max Layer Thickness= 3.402823E+38
Number of Layers= 5

--- FLATROCKRN.f01 (steady flow) ---

Flow Title=Flow
Program Version=6.20
Number of Profiles= 1
Profile Names=P100yr
River Rch & RM=FLATROCKRN,Main            ,12259
     499
River Rch & RM=FLATROCKRN,Main            ,9985
     590
River Rch & RM=FLATROCKRN,Main            ,7807
     759
River Rch & RM=FLATROCKRN,Main            ,4814
     850
Boundary for River Rch & Prof#=FLATROCKRN,Main            , 1
Up Type= 0
Dn Type= 3
Dn Slope=0.08459
DSS Import GetInterval= 0
DSS Import GetPeak= 0
DSS Import FillOption= 0

--- FLATROCKRN.g01 (geometry) ---

Geom Title=Geometry
Program Version=6.20

River Reach=FLATROCKRN      ,Main
Reach XY= 30
2413821.61332457712152.8770690242414211.36970337712395.416728841
     2414535.617      712803.059     2414668.668      713215.295
     2414566.238      713555.139     2414623.455      713956.537
     2414798.443      714131.094     2414785.396      714318.817
2414900.25066154714469.8193384562414857.71551361714650.716459174
2415018.71345917714983.601513609 2414960.7030672  715167.2251201
2415103.72936487715411.1249383762415076.18556625715664.749402932
2414929.55507258715808.0800275572415102.49219763716843.913808089
     2414958.939      717284.215     2415061.436      717788.683
2414908.10794596717974.6971020712414920.11265155718162.069090724
2414483.82951361 718676.07170413     2414564.598      718880.264
     2414370.087      719315.4012414520.28628993719571.353592014
2414336.51064247  719929.3889958     2414577.336      720223.738
2414743.39871598      721236.6222414530.99166745721748.113688127
     2414587.578      722109.302     2414462.881       722783.16

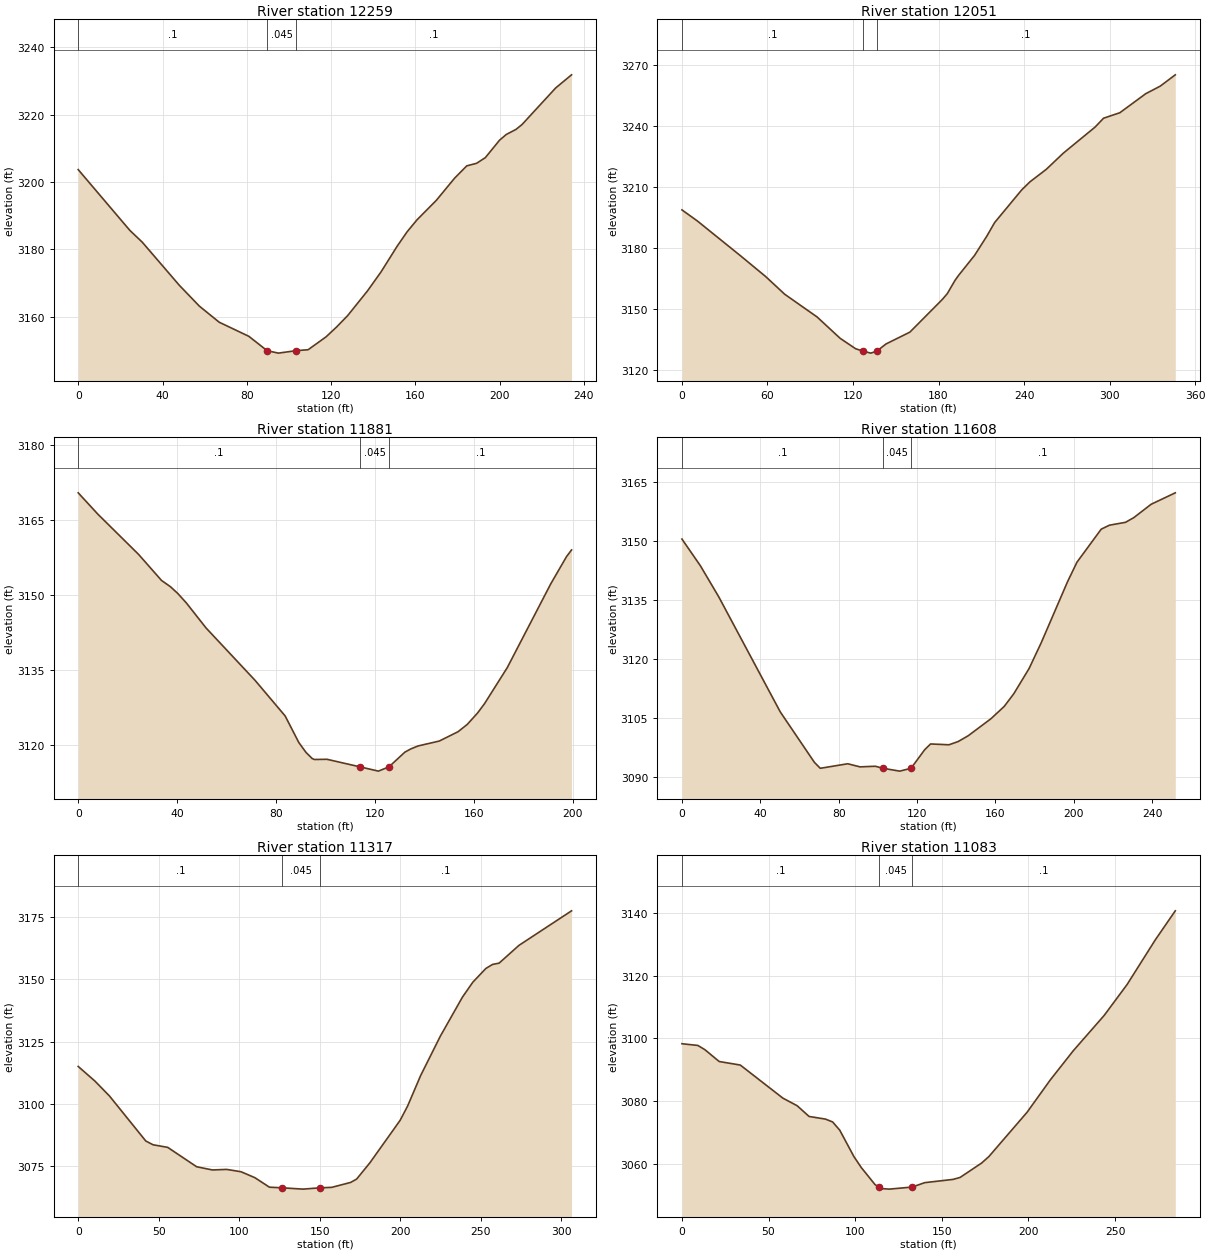
Type RM Length L Ch R = 1 ,12259   ,206.5,207.5,208.1
XS GIS Cut Line= 2
2413799.30542198712250.0978835682413922.09048313712050.820231255
#Sta/Elev= 30
       0 3203.69    24.5 3185.65    30.4 3182.14    48.1 3169.26    57.5 3163.15
    66.9 3158.38      81 3154.18   89.663149.919      95  3149.2  103.223149.919
   109.1 3150.21   117.6 3154.03   122.6 3156.95   127.9 3160.37   137.3  3167.7
   143.7 3173.32   151.4 3180.99   156.1 3185.25   160.8  3188.8   169.9 3194.54
   178.6 3201.14   184.4 3204.81     189 3205.55   193.2 3207.24   199.9  3212.4
   203.1 3214.11   207.7 3215.61   210.6 3217.07   226.6 3227.95   234.1 3231.83
#Mann= 3, -1 ,  0
       0     0.1       0   89.66   0.045       0  103.22     0.1       0
Bank Sta=89.66,103.22
XS Rating Curve= 0 ,0
Exp/Cntr(USF)=0,0
Exp/Cntr=0.3,0.1

Type RM Length L Ch R = 1 ,12051   ,170.4,170.6,170.5
XS GIS Cut Line= 3
2413937.04017869712363.8990529842414089.87996713712193.149049639
2414170.44859783 712108.33663802
#Sta/Elev= 30
       0 3198.79    10.7 3193.41    41.2 3176.18    58.7 3166.06    72.1 3157.34
    94.8 3146.19     111 3135.68   121.8 3130.58  126.853129.423   132.5 3128.41
  136.823129.423   143.2 3132.93   159.9 3138.72   182.6 3154.73   186.2 3157.68
   191.5 3164.08   193.9 3166.45   205.3 3176.44   213.8 3185.79   219.4 3192.59
   238.3 3208.56   244.1 3212.55   255.7 3218.77   267.5 3226.63   289.8 3239.45
   295.8 3243.84   307.2 3246.52   325.4 3255.89   335.5 3259.57   346.1 3265.15
#Mann= 3, -1 ,  0
       0     0.1       0  126.85   0.045       0  136.82     0.1       0
Bank Sta=126.85,136.82
XS Rating Curve= 0 ,0
Exp/Cntr(USF)=0,0
Exp/Cntr=0.3,0.1

Type RM Length L Ch R = 1 ,11881   ,269.4,272.2,272.8
XS GIS Cut Line= 3
2414058.99307624712446.9599199632414117.65861468712413.216664976
  2414205.488747712314.947072459
#Sta/Elev= 30
       0 3170.46       8 3166.16    24.4 3158.14    33.7 3152.91    37.3 3151.66
    40.3 3150.29    43.7 3148.43    51.7  3143.4    71.5 3132.92    83.7 3125.77
    89.2 3120.47    92.1 3118.49    94.6 3117.26    95.5 3117.06   100.6  3117.1
  113.92 3115.59   121.4 3114.73  125.68 3115.59   132.1 3118.53   134.6  3119.2
   137.5 3119.78     146 3120.75   153.6 3122.62   157.3 3124.07   161.5 3126.37
   164.3 3128.23   173.5 3135.45   191.1 3152.24   197.5 3157.71   199.5 3159.02
#Mann= 3, -1 ,  0
       0     0.1       0  113.92   0.045       0  125.68     0.1       0
Bank Sta=113.92,125.68
XS Rating Curve= 0 ,0
Exp/Cntr(USF)=0,0
Exp/Cntr=0.3,0.1

Type RM Length L Ch R = 1 ,11608   ,282.7,291.2,289.1
XS GIS Cut Line= 3
 2414212.1720617712638.2475184572414370.01736636712540.817855611
2414386.62616789712476.675721638
#Sta/Elev= 30
       0 3150.55     9.4 3143.78    18.8 3135.87    50.2 3106.64    67.6 3093.85
    70.6 3092.33    84.6 3093.48    90.9 3092.69    98.7 3092.85  102.68 3092.32
   111.2 3091.61  116.933092.331   123.9 3097.05   126.9 3098.51   136.3  3098.3
     141 3099.13   146.1 3100.59   157.7 3104.91   164.5 3108.05   169.4 3111.28
   177.2 3117.69   183.3 3124.13   196.8  3139.7   201.6 3144.66     214 3153.06
   218.2 3154.07   226.4  3154.8   230.6 3155.98   239.5 3159.39   251.8 3162.29
#Mann= 3, -1 ,  0
       0     0.1       0  102.68   0.045       0  116.93     0.1       0
Bank Sta=102.68,116.93
XS Rating Curve= 0 ,0
Exp/Cntr(USF)=0,0
Exp/Cntr=0.3,0.1

Type RM Length L Ch R = 1 ,11317   ,227.2,233.7,233.8
XS GIS Cut Line= 3
2414374.95376361712824.4959616852414556.31672841712729.542540382
2414656.54918656712711.575620958
#Sta/Elev= 30
       0 3115.07    10.4 3109.19    19.4 3103.24      42 3085.16    46.5 3083.65
    55.6 3082.61    73.6 3074.83    83.4 3073.55    92.3 3073.77   101.2 3072.82
   109.7 3070.48   118.8 3066.64  126.843066.385   139.7 3065.86  150.273066.385
   157.5 3066.57   169.3 3068.56     173  3069.9   181.2 3076.41     200 3093.45
   204.7 3099.25   212.7 3111.35   224.9 3127.12   238.7 3142.86   245.2 3148.89
   253.3 3154.39   257.4 3155.98   261.5 3156.51   273.8 3163.62   306.5 3177.49
#Mann= 3, -1 ,  0
       0     0.1       0  126.84   0.045       0  150.27     0.1       0
Bank Sta=126.84,150.27
XS Rating Curve= 0 ,0
Exp/Cntr(USF)=0,0
Exp/Cntr=0.3,0.1

Type RM Length L Ch R = 1 ,11083   ,120,117.5,110.7
XS GIS Cut Line= 3
2414419.22252897713003.6839797092414590.76571724 712966.03900307
2414689.30131224712919.003030841
#Sta/Elev= 30
       0 3098.29     9.2 3097.74    13.3 3096.37    21.5 3092.61    33.7 3091.48
    58.3 3080.91    66.5  3078.5    73.4 3075.07    82.9 3074.22      87 3073.31
    91.1  3070.7    99.3 3062.24   103.6 3058.71   111.5  3053.3  113.853052.527
   115.6 3052.03   119.7 3051.87  132.823052.527   140.2 3053.94   156.6 3054.98
   160.6 3055.61     173  3060.2   177.2 3062.27   199.3 3076.45   212.6  3086.7
   225.9 3096.04   243.7 3107.29     257 3117.21   273.3 3131.48   284.8 3140.72
#Mann= 3, -1 ,  0
       0     0.1       0  113.85   0.045       0  132.82     0.1       0
Bank Sta=113.85,132.82
XS Rating Curve= 0 ,0
Exp/Cntr(USF)=0,0
Exp/Cntr=0.3,0.1

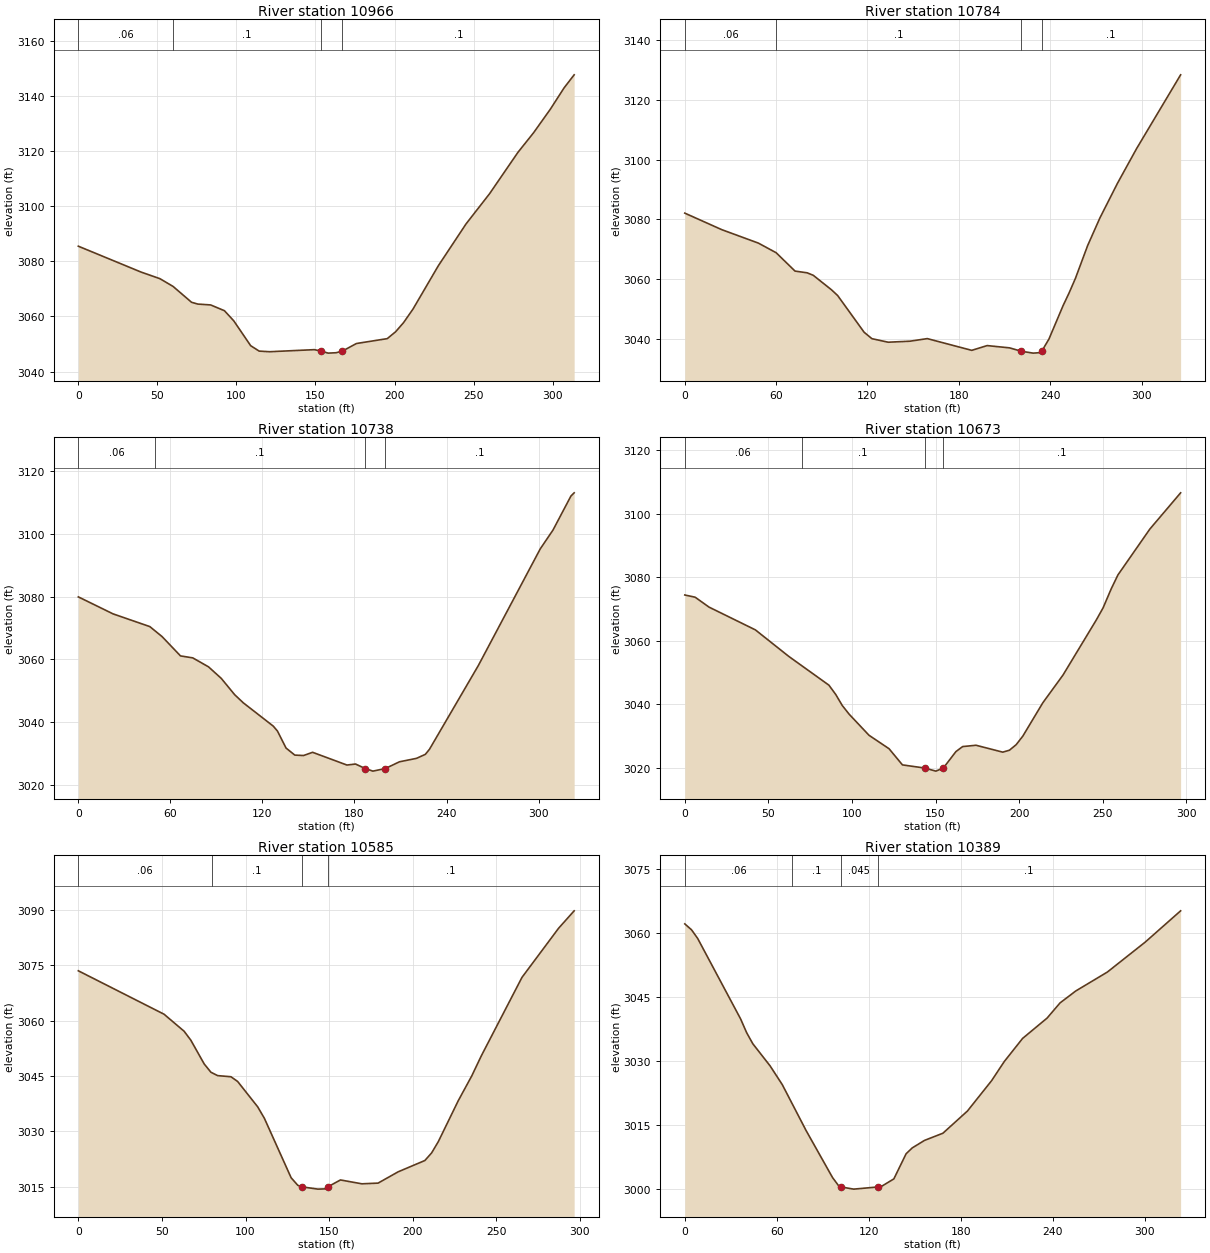
Type RM Length L Ch R = 1 ,10966   ,174.6,182.2,192.6
XS GIS Cut Line= 4
2414460.62234461713124.4108653342414548.73244767713120.005360181
2414656.66732392713022.3499959552414727.88965723712986.371703872
#Sta/Elev= 30
       0 3085.49    39.6 3076.12    51.6  3073.7    59.9  3070.9    71.6 3065.14
    75.6 3064.48    83.7 3064.17    92.4 3062.08    98.3 3058.41     109 3049.38
   114.4 3047.41     121 3047.19   149.3 3047.94   153.6 3047.41     158 3046.68
     163 3046.82  167.043047.427   175.9 3050.17   195.4 3051.94   200.7 3054.45
   205.7 3057.75   211.7  3062.7   227.7  3078.4   245.2 3093.56   260.1 3104.54
     278 3119.52   287.9 3126.64   298.5 3135.18   307.3 3143.01   313.6 3147.69
#Mann= 4, -1 ,  0
       0    0.06       0      60     0.1       0   153.6   0.045       0
  167.04     0.1       0
Bank Sta=153.6,167.04
XS Rating Curve= 0 ,0
Exp/Cntr(USF)=0,0
Exp/Cntr=0.3,0.1

Type RM Length L Ch R = 1 ,10784   ,45.2,45.4,46.8
XS GIS Cut Line= 4
2414463.86346588713158.5197258372414574.65376214713162.762064132
2414682.36610398713245.562257043   2414760.90873713237.247734591
#Sta/Elev= 30
       0 3082.08    24.3 3076.53    48.3 3072.03      60  3068.8    72.4 3062.64
    80.4 3062.05    84.4 3061.22    96.4 3056.34   100.4 3054.44   117.8 3042.11
   122.9 3039.96   133.6 3038.77   147.9 3039.11   159.3 3039.98   188.5 3036.04
   198.6 3037.64   213.3 3036.88  221.123035.733   228.8 3035.11   233.9 3035.29
  234.463035.733   239.2 3039.83   248.5 3051.05   252.4 3055.26   256.6  3060.2
   264.6 3071.16   272.7 3080.49   284.3 3092.17   296.8 3103.75   325.7 3128.48
#Mann= 4, -1 ,  0
       0    0.06       0      60     0.1       0  221.12   0.045       0
  234.46     0.1       0
Bank Sta=221.12,234.46
XS Rating Curve= 0 ,0
Exp/Cntr(USF)=0,0
Exp/Cntr=0.3,0.1

Type RM Length L Ch R = 1 ,10738   ,69.5,65.4,60
XS GIS Cut Line= 4
 2414469.5999548713172.8421430692414546.68999032713176.001570754
2414659.21628228713288.3695799372414746.25820363713289.578495512
#Sta/Elev= 30
       0 3079.94    22.6 3074.53    46.6 3070.47    54.6 3067.28    66.6 3061.13
    74.6  3060.5    84.9 3057.63    93.2 3053.95   101.9 3048.77   107.5 3046.19
   127.1 3038.74   129.8 3037.18   135.4 3031.76   141.1 3029.52   146.8 3029.38
   152.7 3030.41   175.1 3026.35   180.7 3026.67  186.993025.243     192 3024.41
  200.143025.243   209.3 3027.38   220.5 3028.49   226.2 3029.76   228.9 3031.38
   260.7 3058.02   301.1 3095.24   309.4 3101.23   321.1 3112.08   323.2  3113.1
#Mann= 4, -1 ,  0
       0    0.06       0      50     0.1       0  186.99   0.045       0
  200.14     0.1       0
Bank Sta=186.99,200.14
XS Rating Curve= 0 ,0
Exp/Cntr(USF)=0,0
Exp/Cntr=0.3,0.1

Type RM Length L Ch R = 1 ,10673   ,89.2,87.9,88.3
XS GIS Cut Line= 2
2414449.99624337713313.5768107062414746.54907697713312.022674766
#Sta/Elev= 30
       0 3074.48     6.2 3073.78    14.5 3070.66    42.2  3063.5    62.2 3055.14
    86.2 3046.08    90.3 3043.14    94.2 3039.67    98.3 3036.94   110.2 3030.29
   122.2 3026.05   130.2 3020.96  143.393019.983   150.2    3019  154.663019.981
   162.2 3025.16   166.2 3026.73   174.2 3027.15   190.2 3024.98   194.2 3025.59
   198.2 3027.32   202.2 3030.02   214.2 3040.55   226.2 3049.23   246.2 3066.65
   250.2 3070.41   255.1 3076.44   259.1  3080.8   278.2 3095.25   296.6 3106.66
#Mann= 4, -1 ,  0
       0    0.06       0      70     0.1       0  143.39   0.045       0
  154.66     0.1       0
Bank Sta=143.39,154.66
XS Rating Curve= 0 ,0
Exp/Cntr(USF)=0,0
Exp/Cntr=0.3,0.1

Type RM Length L Ch R = 1 ,10585   ,195.8,196.1,194.3
XS GIS Cut Line= 2
2414440.92473712713400.4037706062414737.47757072713398.849634666
#Sta/Elev= 30
       0 3073.54    51.3 3061.76    63.3 3057.14    67.3 3054.72    75.3 3048.28
    79.3 3046.04    83.3 3045.12    91.3 3044.81    95.3 3043.53   107.3 3036.65
   111.3 3033.54   127.3 3017.42   131.3 3015.37  133.633014.965   143.3 3014.34
   147.3  3014.4  149.283014.964   156.8 3016.83   169.6 3015.78   179.3 3015.97
   191.3 3019.03   207.3  3022.1   211.3 3024.14   215.3 3027.18   227.3 3038.34
   235.3    3045   241.2  3050.6   265.4 3071.76   287.3 3085.08   296.6  3089.8
#Mann= 4, -1 ,  0
       0    0.06       0      80     0.1       0  133.63   0.045       0
  149.28     0.1       0
Bank Sta=133.63,149.28
XS Rating Curve= 0 ,0
Exp/Cntr(USF)=0,0
Exp/Cntr=0.3,0.1

Type RM Length L Ch R = 1 ,10389   ,179.6,180.2,177.1
XS GIS Cut Line= 3
2414451.81918684713593.7478808032414694.74456927713588.464395402
2414757.31719637713537.791251005
#Sta/Elev= 30
       0 3062.03     4.4 3060.64     8.4 3058.62    36.4 3039.77    40.4  3036.5
    44.4 3033.93    55.7 3028.73    63.6 3024.36    79.2 3013.56    96.4 3002.58
   100.4 3000.64  102.06 3000.37   110.2 2999.87  125.73 3000.37   128.4 3000.53
   136.4 3002.27   144.4 3008.16   148.4 3009.53   156.4 3011.29   168.4 3012.97
   184.4 3018.17   200.2  3025.3   208.4 3029.75   220.4 3035.19   236.4 3039.96
   244.8  3043.5   255.1 3046.31   275.7 3050.74   300.4 3057.76   323.5 3065.09
#Mann= 4, -1 ,  0
       0    0.06       0      70     0.1       0  102.06   0.045       0
  125.73     0.1       0
Bank Sta=102.06,125.73
XS Rating Curve= 0 ,0
Exp/Cntr(USF)=0,0
Exp/Cntr=0.3,0.1

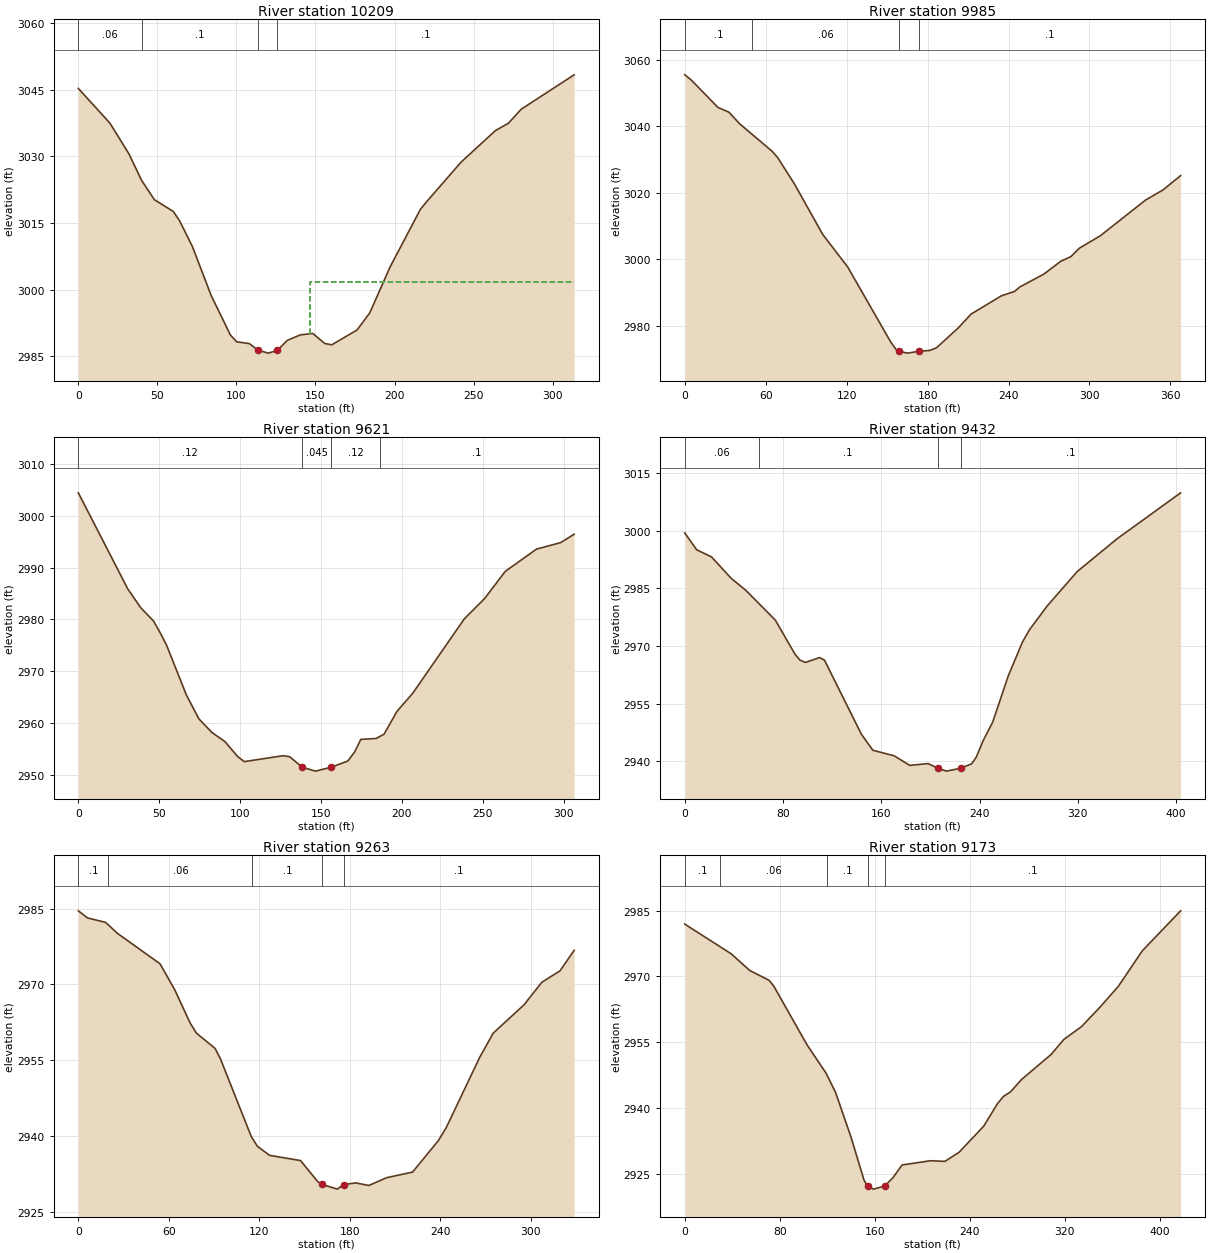
Type RM Length L Ch R = 1 ,10209   ,223.9,223.7,220.6
XS GIS Cut Line= 3
2414480.20966579713762.6595626032414715.79070686713747.578763501
2414772.69810632713694.930011594
#Sta/Elev= 30
       0  3045.3      20 3037.47      32 3030.57      40  3024.6    48.1 3020.24
    60.1 3017.58    64.1 3015.44    72.1 3009.73      84 2998.67    96.2 2989.76
   100.2 2988.23   108.2 2987.82  113.742986.321   120.2 2985.68   125.92986.318
   132.2 2988.55   140.3 2989.78   148.3 2990.12   155.8 2987.86   160.3 2987.55
   176.3  2990.9   184.3 2994.73   197.2  3005.1   216.4 3018.09   220.4 3019.82
     242 3028.67   263.8  3035.8     272 3037.45   280.2 3040.64   313.6 3048.36
#Mann= 4, -1 ,  0
       0    0.06       0      40     0.1       0  113.74   0.045       0
   125.9     0.1       0
#XS Ineff= 2 , 0
                          146.83         3001.62
Permanent Ineff=
       F       F
Bank Sta=113.74,125.9
XS Rating Curve= 0 ,0
Exp/Cntr(USF)=0,0
Exp/Cntr=0.3,0.1

Type RM Length L Ch R = 1 ,9985    ,359,364.2,364.3
XS GIS Cut Line= 4
2414467.61547887713989.7094336152414538.17880843713995.741231681
2414722.48293505 713939.570828572414788.68784953713859.272908759
#Sta/Elev= 30
       0 3055.45     4.6 3053.96    24.6 3045.65    32.7 3044.23    40.7 3040.72
    64.8 3032.45    68.8 3030.61    81.3 3022.63   102.2 3007.51   120.8 2997.66
   152.4 2975.32   156.5 2972.94  158.84 2972.35   164.9 2971.78   173.8 2972.34
   181.6 2972.59   186.6 2973.38   202.7 2979.34   212.3 2983.53   234.7 2989.01
   244.4 2990.31   248.5  2991.7   266.2 2995.54   278.7 2999.38   286.3 3000.82
   292.5 3003.32   308.1 3007.07   341.6  3017.8   354.5 3020.83   367.6 3025.16
#Mann= 4, -1 ,  0
       0     0.1       0      50    0.06       0  158.84   0.045       0
   173.8     0.1       0
Bank Sta=158.84,173.8
XS Rating Curve= 0 ,0
Exp/Cntr(USF)=0,0
Exp/Cntr=0.3,0.1

Type RM Length L Ch R = 1 ,9621    ,193.9,188.7,184.6
XS GIS Cut Line= 3
2414633.68058089714256.0658530192414810.07446851 714249.24285282
 2414914.9658973 714172.43306649
#Sta/Elev= 30
       0 3004.39    30.5 2985.92    38.5 2982.29    46.5  2979.7    50.5  2977.5
    54.5 2975.09    66.8 2965.46    74.5 2960.88    82.6 2958.24    90.6  2956.5
    98.6 2953.57   102.6 2952.63   126.6 2953.77   130.6 2953.58  138.512951.538
   146.6  2950.8  156.182951.539   166.6 2952.75   170.9 2954.54   174.6 2956.91
   184.1 2957.09     189 2957.91   196.9 2962.28   206.7 2965.79   238.6 2980.12
   251.1 2984.02   263.9 2989.26   283.2 2993.55   298.1  2994.8   306.5 2996.42
#Mann= 4, -1 ,  0
       0    0.12       0  138.51   0.045       0  156.18    0.12       0
  186.53     0.1       0
Bank Sta=138.51,156.18
XS Rating Curve= 0 ,0
Exp/Cntr(USF)=0,0
Exp/Cntr=0.3,0.1

Type RM Length L Ch R = 1 ,9432    ,161.6,168.9,174.6
XS GIS Cut Line= 3
2414658.46327043714459.6514376652414789.44033434714456.937553317
2415020.08709717714311.611307456
#Sta/Elev= 30
       0 2999.48     9.7 2995.09    21.7 2993.25    37.7 2987.68    49.7 2984.51
    73.7 2976.75    89.7 2967.88    93.7 2966.33    98.2 2965.72   109.7 2966.98
   113.7 2966.32   143.7 2947.02   153.1 2942.81   170.5 2941.36   183.1 2938.87
   198.1 2939.34  205.852938.147   213.1 2937.37  224.932938.147   233.5 2939.28
   237.2 2940.98     243 2945.42   250.6 2950.13   263.3  2962.2   274.9 2971.06
   280.7  2974.3     295 2980.45   319.4 2989.41   351.7 2997.92   403.6 3009.95
#Mann= 4, -1 ,  0
       0    0.06       0      60     0.1       0  205.85   0.045       0
  224.93     0.1       0
Bank Sta=205.85,224.93
XS Rating Curve= 0 ,0
Exp/Cntr(USF)=0,0
Exp/Cntr=0.3,0.1

Type RM Length L Ch R = 1 ,9263    ,92.2,90.2,88.9
XS GIS Cut Line= 4
2414698.10622287714543.8820922072414793.30832434714537.233056548
2414907.24861722714560.5046813532415012.42427218714508.823540553
#Sta/Elev= 30
       0 2984.57     6.1 2983.17    18.1 2982.28    26.1 2980.08    54.2 2974.09
      64 2968.92    74.2 2962.36    78.3 2960.37    90.7 2957.35    94.2 2955.33
   114.7 2939.92   118.8 2937.97   126.9 2936.18   147.4 2935.15   158.8 2930.99
  161.862930.421   171.8  2929.5   175.9  2930.4   184.1 2930.73   192.7 2930.22
   204.5 2931.76   221.7 2932.87   238.8 2939.09     244 2941.64   266.2 2955.55
   275.2 2960.36   295.6 2965.96   307.5 2970.45   319.5 2972.69   328.9 2976.75
#Mann= 5, -1 ,  0
       0     0.1       0      20    0.06       0  115.43     0.1       0
  161.86   0.045       0   175.9     0.1       0
Bank Sta=161.86,175.9
XS Rating Curve= 0 ,0
Exp/Cntr(USF)=0,0
Exp/Cntr=0.3,0.1

Type RM Length L Ch R = 1 ,9173    ,172.8,170.3,169.7
XS GIS Cut Line= 3
2414693.24586846714647.4413926092414954.99570701714637.464122398
2415077.51197435714541.225755446
#Sta/Elev= 30
       0  2981.9      39 2975.14    54.8 2971.31      71 2969.08      75 2967.74
     103 2954.35     119  2947.9     127 2943.52     140 2933.33     151 2923.48
  154.022922.141     159 2921.44  168.352922.139   175.1 2923.97   183.1 2926.96
   207.1 2927.92   219.1 2927.77   231.1 2929.86   251.8  2935.8   263.4 2940.94
   268.5  2942.6   274.4 2943.63   283.8 2946.48   308.6 2952.16   319.4 2955.61
   334.2 2958.51   349.9 2962.99   365.2 2967.69   385.4  2975.8   417.7 2984.93
#Mann= 5, -1 ,  0
       0     0.1       0      30    0.06       0     120     0.1       0
  154.02   0.045       0  168.35     0.1       0
Bank Sta=154.02,168.35
XS Rating Curve= 0 ,0
Exp/Cntr(USF)=0,0
Exp/Cntr=0.3,0.1

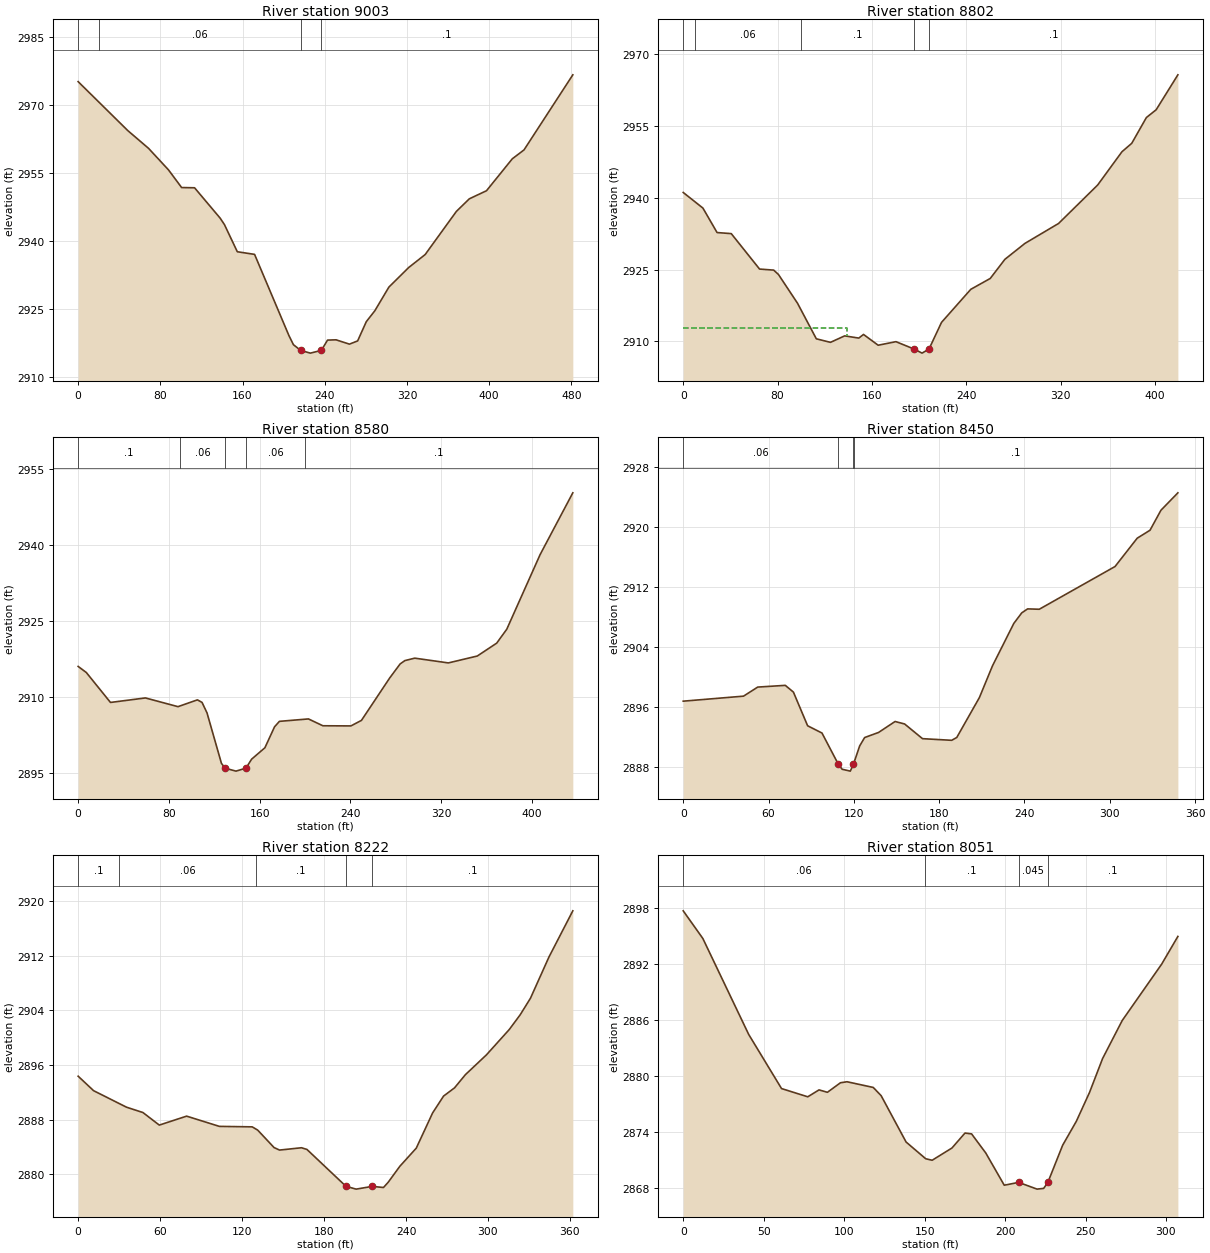
Type RM Length L Ch R = 1 ,9003    ,199,200.4,197.7
XS GIS Cut Line= 3
2414696.18529886714823.2930268252414799.98719237714835.875021142
2415160.55775516714726.252776075
#Sta/Elev= 30
       0 2975.06    48.3 2964.28    68.5 2960.37    87.9 2955.63   100.7 2951.73
   113.3 2951.68   138.2 2944.99   142.4 2943.56   154.9 2937.59   171.7 2937.01
   205.1 2919.14   209.5 2917.12  216.482915.871     226 2915.26  236.722915.872
   242.7 2918.13     251 2918.19     264 2917.24     272 2917.95   280.4 2922.18
   288.7 2924.58   302.4  2929.8   321.7 2934.12   337.7 2936.97   368.1 2946.48
   380.7 2949.25   397.4 2951.03   422.5 2958.06   433.9 2960.02   481.4 2976.56
#Mann= 4, -1 ,  0
       0     0.1       0      20    0.06       0  216.48   0.045       0
  236.72     0.1       0
Bank Sta=216.48,236.72
XS Rating Curve= 0 ,0
Exp/Cntr(USF)=0,0
Exp/Cntr=0.3,0.1

Type RM Length L Ch R = 1 ,8802    ,224.3,222.3,219.6
XS GIS Cut Line= 3
2414811.53634502714972.4420605572414965.35704893714979.795958932
2415222.05062612 714912.97269814
#Sta/Elev= 30
       0  2941.1    16.7 2937.84    28.7 2932.73    40.7 2932.51    64.7 2925.11
    76.7 2924.89    80.7 2923.98    96.9 2917.96   112.8 2910.55   124.8 2909.81
   136.8 2911.16   148.8  2910.7   152.8 2911.46   165.2 2909.21   180.3 2909.95
  195.712908.404   202.4 2907.56  208.272908.405   218.9 2913.98   243.7 2920.88
   260.2 2923.15   272.6 2927.14   289.6 2930.47   318.1 2934.63   351.2 2942.65
   371.8  2949.6   380.1 2951.36   392.5 2956.74   400.8 2958.37   419.2 2965.66
#Mann= 5, -1 ,  0
       0     0.1       0      10    0.06       0     100     0.1       0
  195.71   0.045       0  208.27     0.1       0
#XS Ineff= 2 , 0
          139.06 2912.88
Permanent Ineff=
       F       F
Bank Sta=195.71,208.27
XS Rating Curve= 0 ,0
Exp/Cntr(USF)=0,0
Exp/Cntr=0.3,0.1

Type RM Length L Ch R = 1 ,8580    ,131,129.7,127.9
XS GIS Cut Line= 2
2414829.40885621715222.3417650672415239.33122539 715073.67971554
#Sta/Elev= 30
       0 2916.11     7.2 2914.91    28.5    2909    59.3 2909.89      88 2908.17
   105.1 2909.51   109.2 2909.01   113.6 2906.93   126.3 2896.99  129.492896.033
   139.1 2895.45   147.92896.034   152.9 2897.81   164.6 2900.06   173.1 2904.19
   177.4 2905.27     203 2905.75   215.7  2904.4   240.4 2904.37   249.7 2905.46
   274.7 2913.86   283.8  2916.6     288 2917.26   296.7 2917.74   326.3  2916.8
   351.8 2918.16   368.9  2920.7   377.8 2923.45   407.2 2938.18     436 2950.36
#Mann= 5, -1 ,  0
       0     0.1       0      90    0.06       0  129.49   0.045       0
   147.9    0.06       0     200     0.1       0
Bank Sta=129.49,147.9
XS Rating Curve= 0 ,0
Exp/Cntr(USF)=0,0
Exp/Cntr=0.3,0.1

Type RM Length L Ch R = 1 ,8450    ,221.6,227.8,231.8
XS GIS Cut Line= 3
2414914.36982896715363.9982587892415032.77388229715274.544722015
2415227.26825062715230.015748213
#Sta/Elev= 30
       0 2896.83    42.4  2897.5    52.4 2898.71    71.8 2898.94    77.5 2898.04
    87.5 2893.55    97.6 2892.58  109.162888.395   111.8 2887.75   117.5  2887.5
  119.682888.396   124.1 2890.86   127.6 2891.98   137.4 2892.66     149 2894.12
   155.7 2893.79   168.3 2891.83   188.8 2891.61   192.4 2891.99   208.3 2897.31
   217.5 2901.54   232.5  2907.2   238.1 2908.61   242.2 2909.14   250.4 2909.09
   303.7 2914.79   319.3 2918.57   328.3 2919.63     336  2922.3   347.9 2924.62
#Mann= 4, -1 ,  0
       0    0.06       0  109.16   0.045       0  119.68    0.06       0
     120     0.1       0
Bank Sta=109.16,119.68
XS Rating Curve= 0 ,0
Exp/Cntr(USF)=0,0
Exp/Cntr=0.3,0.1

Type RM Length L Ch R = 1 ,8222    ,168,171.3,171
XS GIS Cut Line= 2
 2414880.8382309715465.3315435482415242.69617152715478.852690315
#Sta/Elev= 30
       0 2894.35    11.3 2892.23    35.4 2889.81    47.4 2889.03    59.4 2887.19
    79.4  2888.5   103.4    2887   127.4 2886.93   131.4 2886.46   143.4  2883.9
   147.4 2883.53   163.5 2883.87   167.5 2883.62  196.06 2878.22   203.5 2877.81
   215.3 2878.21   223.5 2878.05   226.9  2878.8   235.5 2881.16   247.5 2883.81
   259.5 2888.98   267.5 2891.44   275.5 2892.64   283.5 2894.58   298.9 2897.48
   315.6 2901.19   323.6 2903.35   331.1 2905.77   344.6 2911.79   362.1 2918.57
#Mann= 5, -1 ,  0
       0     0.1       0      30    0.06       0     130     0.1       0
  196.06   0.045       0   215.3     0.1       0
Bank Sta=196.06,215.3
XS Rating Curve= 0 ,0
Exp/Cntr(USF)=0,0
Exp/Cntr=0.3,0.1

Type RM Length L Ch R = 1 ,8051    ,246.4,244.3,241.4
XS GIS Cut Line= 2
2414868.16720107715593.3978384182415170.12308647715650.889924966
#Sta/Elev= 30
       0 2897.67    12.2 2894.71    40.7 2884.44    61.1 2878.65    77.4 2877.77
    84.4 2878.51    89.6 2878.25    97.7 2879.27   101.8 2879.38   118.1 2878.77
     123 2877.89   138.5 2872.93   150.7 2871.14   154.7 2870.98     167 2872.29
   175.1 2873.89   179.2  2873.8     188 2871.76   199.5 2868.31   208.5 2868.61
   219.9 2867.89     224 2867.97   226.6 2868.61   235.8 2872.59   244.3 2875.15
   252.5 2878.24   260.6 2881.86   272.8 2885.93   297.3 2891.96   307.4 2894.93
#Mann= 4, -1 ,  0
       0    0.06       0     150     0.1       0   208.5   0.045       0
   226.6     0.1       0
Bank Sta=208.5,226.6
XS Rating Curve= 0 ,0
Exp/Cntr(USF)=0,0
Exp/Cntr=0.3,0.1

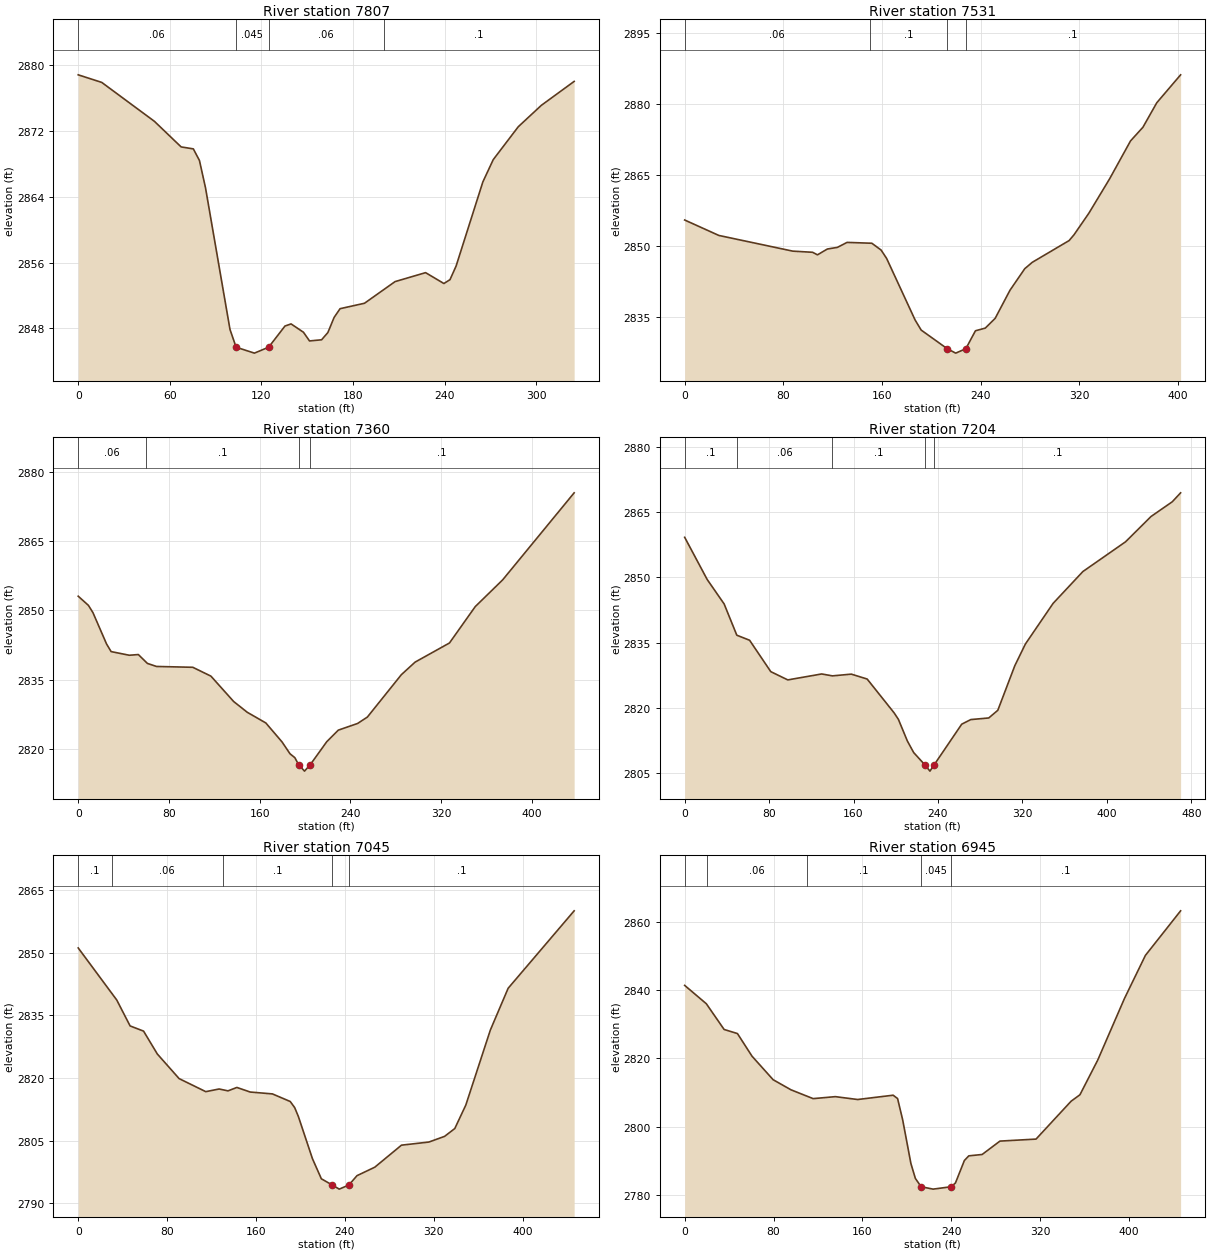
Type RM Length L Ch R = 1 ,7807    ,276.9,275.4,274.9
XS GIS Cut Line= 3
2414812.76016301715801.6334128382415069.77299536715807.335532128
 2415124.7806591715767.837128247
#Sta/Elev= 30
       0 2878.82    15.4  2877.9    49.9 2873.17    67.4 2870.06    75.4 2869.82
    79.4 2868.41    83.4 2865.06    99.4 2847.88   103.4 2845.72   115.4    2845
  124.742845.722   135.4 2848.29   139.4 2848.55   147.5 2847.54   151.5 2846.48
   159.4 2846.62   163.5  2847.5   167.6 2849.34   171.5  2850.4   187.5 2851.06
   207.5 2853.69   227.5 2854.78   239.5 2853.46   243.5 2853.93   247.5 2855.59
     265  2865.8   271.8 2868.51   288.2 2872.51   303.3 2875.11   324.8 2878.02
#Mann= 4, -1 ,  0
       0    0.06       0   103.4   0.045       0  124.74    0.06       0
     200     0.1       0
Bank Sta=103.4,124.74
XS Rating Curve= 0 ,0
Exp/Cntr(USF)=0,0
Exp/Cntr=0.3,0.1

Type RM Length L Ch R = 1 ,7531    ,172.5,171.8,170.1
XS GIS Cut Line= 3
2414768.43776012716063.502677402 2415101.5401805716068.038266258
2415166.21855073716043.762825614
#Sta/Elev= 30
       0 2855.54    27.7 2852.28    87.7 2848.96   103.7 2848.72   107.7 2848.18
   115.7 2849.41   123.8 2849.75   131.7 2850.81   151.8 2850.63   159.3 2849.19
   163.8 2847.41   186.9  2834.4   191.8 2832.28  212.962828.337   219.8 2827.41
     2282828.336   235.8 2832.13   243.8  2832.7   251.8 2834.76   263.8 2840.69
   275.8 2845.25   281.9  2846.6   311.8  2851.2   315.8 2852.44   327.8 2856.98
   344.5 2864.19   361.6 2872.26   371.6 2875.13   382.9 2880.33   402.2 2886.22
#Mann= 4, -1 ,  0
       0    0.06       0     150     0.1       0  212.96   0.045       0
     228     0.1       0
Bank Sta=212.96,228
XS Rating Curve= 0 ,0
Exp/Cntr(USF)=0,0
Exp/Cntr=0.3,0.1

Type RM Length L Ch R = 1 ,7360    ,155,155.2,154.9
XS GIS Cut Line= 3
2414759.19547799716241.5574986762414918.03737304716244.333705084
 2415179.3501361 716148.55238989
#Sta/Elev= 30
       0 2853.08       9  2851.1      13 2849.53      25 2842.76      29 2841.12
      45 2840.33      53 2840.48      61 2838.57      69 2837.91     101 2837.73
     117 2835.82     137 2830.35     149 2828.02   165.4 2825.71   179.7 2821.61
   186.7 2819.06     191 2818.21  194.292816.688   199.5 2815.31  204.532816.689
   219.1 2821.66   229.3 2824.16   246.3  2825.6   254.9 2826.98   284.9 2836.14
     297 2838.85   327.3 2842.98     350 2850.83   374.2 2856.61   437.2  2875.4
#Mann= 4, -1 ,  0
       0    0.06       0      60     0.1       0  194.29   0.045       0
  204.53     0.1       0
Bank Sta=194.29,204.53
XS Rating Curve= 0 ,0
Exp/Cntr(USF)=0,0
Exp/Cntr=0.3,0.1

Type RM Length L Ch R = 1 ,7204    ,156.8,159.5,160.7
XS GIS Cut Line= 4
2414770.97730273716408.8419065092414967.62055609716389.707673185
2415058.17816201716354.6267988182415231.95086527716332.599273053
#Sta/Elev= 30
       0 2859.24    21.3 2849.53    37.4 2843.88    49.4 2836.68    61.5 2835.52
    81.6 2828.28    97.7 2826.38   129.8 2827.75     140 2827.31   157.9 2827.71
   172.9 2826.58   198.4  2818.8   202.5 2817.29     211  2812.3     217 2809.63
  227.332806.877   232.4 2805.36  236.562806.875   262.5 2816.18   271.1 2817.24
   288.1 2817.61   296.7 2819.38   312.8 2829.65   322.8 2834.64   349.1 2844.02
   377.3 2851.35   417.7  2858.2   441.9 2864.04     462 2867.43   469.9 2869.49
#Mann= 5, -1 ,  0
       0     0.1       0      50    0.06       0     140     0.1       0
  227.33   0.045       0  236.56     0.1       0
Bank Sta=227.33,236.56
XS Rating Curve= 0 ,0
Exp/Cntr(USF)=0,0
Exp/Cntr=0.3,0.1

Type RM Length L Ch R = 1 ,7045    ,98.7,99.4,98.9
XS GIS Cut Line= 2
2414785.45399395716531.1126428852415231.45895692716516.055187165
#Sta/Elev= 30
       0 2851.19    34.7  2838.7    46.7 2832.49    58.8 2831.25    71.2 2825.76
    90.8 2819.86   114.8 2816.73   126.8 2817.37   134.8 2816.92   142.8 2817.74
   154.8 2816.64   174.8 2816.19   190.8 2814.37   194.8 2812.91   198.1 2810.79
   210.8 2800.66   218.8 2795.84  228.592794.352   234.9 2793.36  243.57 2794.35
   250.9 2796.59   266.9 2798.62   290.9  2803.9   315.6 2804.65   329.7 2806.01
   338.9 2807.89   348.8 2813.51   370.9 2831.51   386.9 2841.52   446.3 2860.09
#Mann= 5, -1 ,  0
       0     0.1       0      30    0.06       0     130     0.1       0
  228.59   0.045       0  243.57     0.1       0
Bank Sta=228.59,243.57
XS Rating Curve= 0 ,0
Exp/Cntr(USF)=0,0
Exp/Cntr=0.3,0.1

Type RM Length L Ch R = 1 ,6945    ,218.1,218.2,214.9
XS GIS Cut Line= 2
 2414800.6549384716628.3193762582415246.65990138716613.261920538
#Sta/Elev= 30
       0 2841.33    19.5 2835.96    35.5 2828.44    47.5 2827.24    60.6 2820.63
    79.6 2813.75    95.6 2810.81   115.6 2808.22   135.6  2808.8   155.6 2807.96
   187.6 2809.22   191.6 2808.24   196.2 2801.98   203.6 2789.23   207.6 2784.89
  212.762782.461   223.6 2781.76  239.83 2782.46   243.7 2783.58   251.7 2790.13
   255.7 2791.49   267.7 2791.89   283.7  2795.8   316.2 2796.39   347.7 2807.45
   355.7 2809.35   371.7 2819.48   395.7 2837.45   414.6 2850.09   446.3 2863.13
#Mann= 5, -1 ,  0
       0     0.1       0      20    0.06       0     110     0.1       0
  212.76   0.045       0  239.83     0.1       0
Bank Sta=212.76,239.83
XS Rating Curve= 0 ,0
Exp/Cntr(USF)=0,0
Exp/Cntr=0.3,0.1