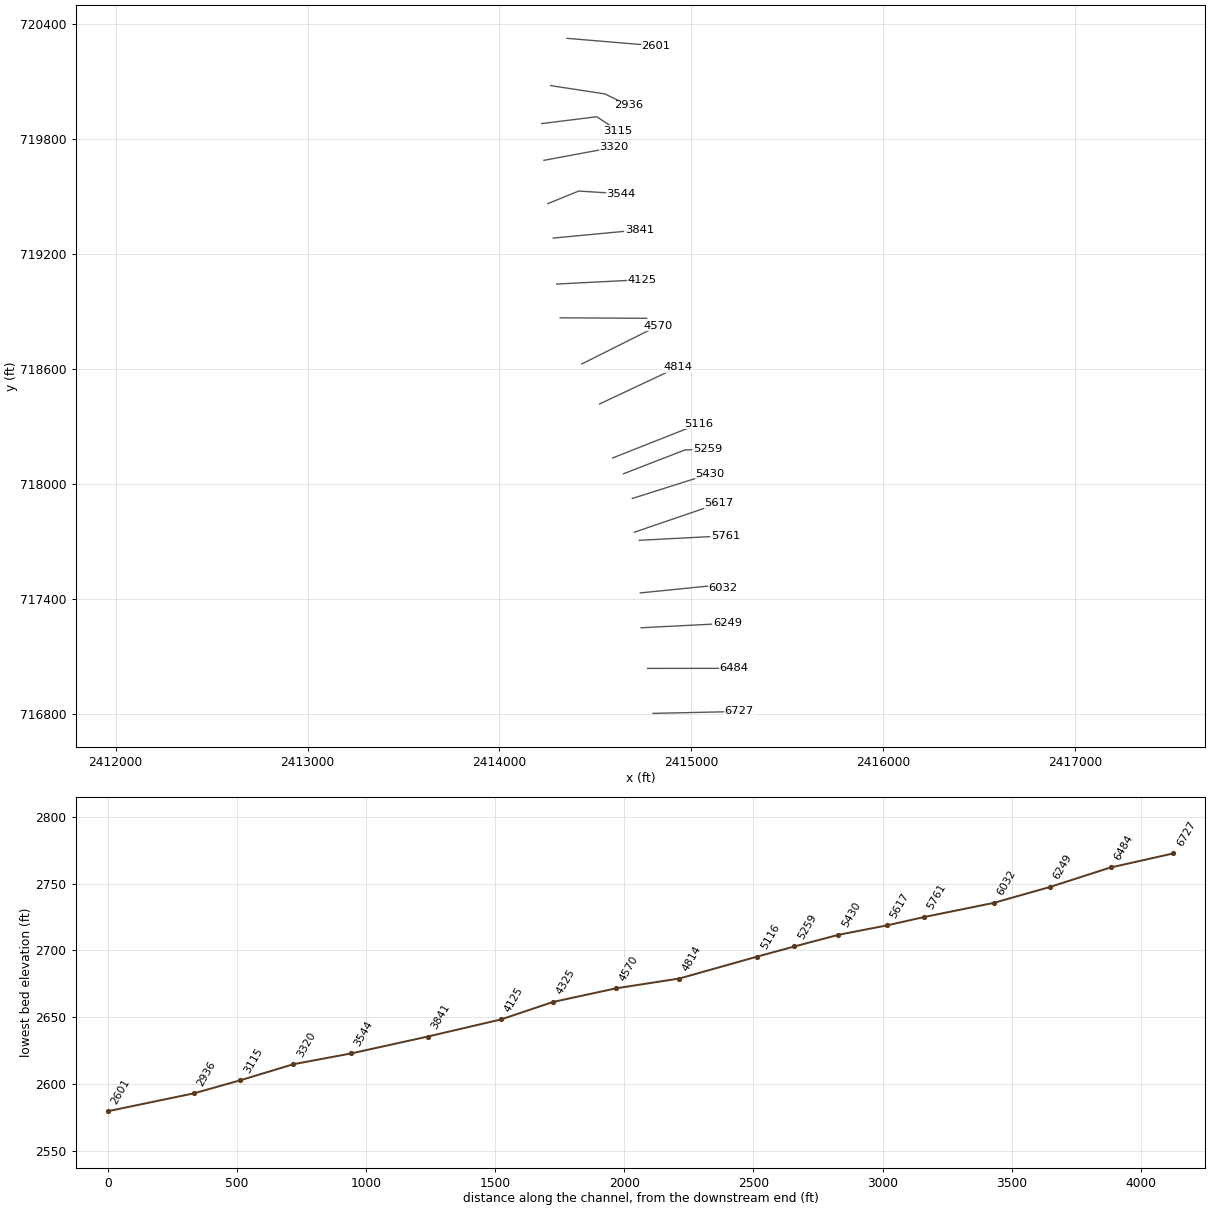
HEC-RAS study FLATROCKRN.prj: FLATROCKRN

--- FLATROCKRN.g01 (geometry) --- (continued)

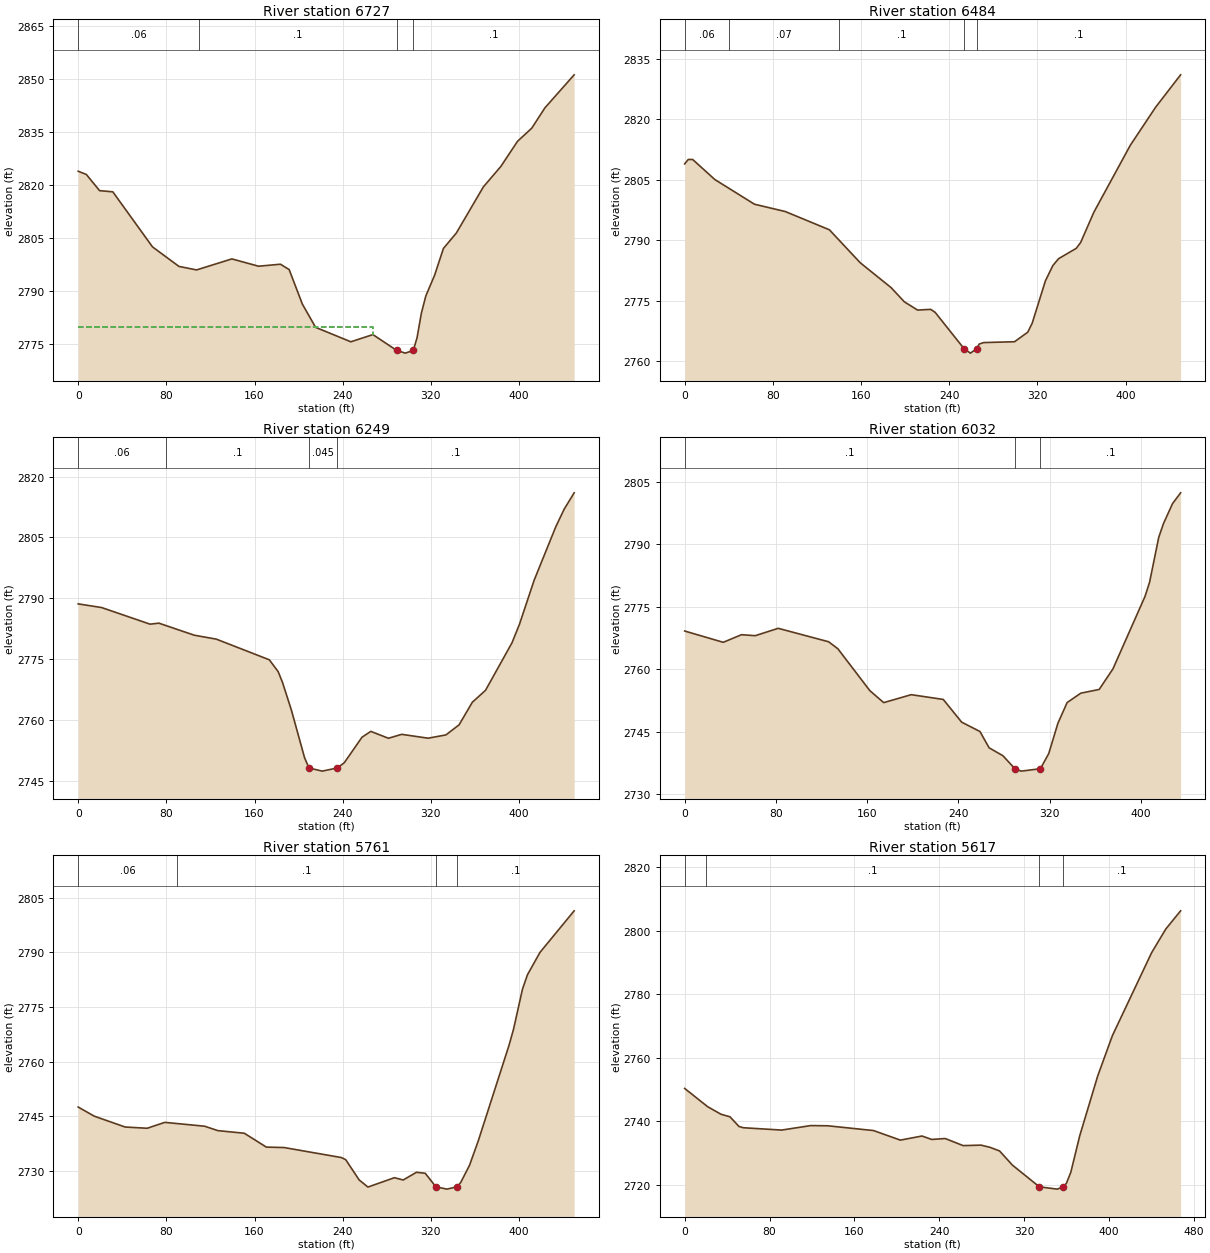
Type RM Length L Ch R = 1 ,6727    ,242.6,243.3,243.3
XS GIS Cut Line= 2
2414800.81000761716805.2987815252415250.70221927716815.147531946
#Sta/Elev= 30
       0 2823.98     7.4 2823.06    19.4 2818.48    31.4 2818.15    67.4 2802.56
    91.4 2797.03   107.4 2796.03   139.4 2799.15   163.7 2797.08   183.5 2797.65
   191.4 2796.13   203.4 2786.35   215.4 2779.77   247.4 2775.68   267.4 2777.72
  288.972773.235   296.8 2772.47  304.012773.236   307.4 2776.74   311.4 2783.82
   315.4 2788.65   323.4 2794.55   331.4 2802.12   343.1 2806.48   367.6 2819.53
   383.5 2825.34   398.6 2832.45   411.5 2836.16   423.5 2841.94     450 2851.28
#Mann= 4, -1 ,  0
       0    0.06       0     110     0.1       0  288.97   0.045       0
  304.01     0.1       0
#XS Ineff= 2 , 0
          267.43  2779.8
Permanent Ineff=
       F       F
Bank Sta=288.97,304.01
XS Rating Curve= 0 ,0
Exp/Cntr(USF)=0,0
Exp/Cntr=0.3,0.1

Type RM Length L Ch R = 1 ,6484    ,237.5,235.2,234.1
XS GIS Cut Line= 2
2414772.85347634 717039.681778332415222.85328861717040.092823389
#Sta/Elev= 30
       0 2808.97     3.3 2810.07     7.3 2810.05    27.3 2805.09    63.3 2798.95
    91.3 2797.13   131.3  2792.6   159.3 2784.41   187.3 2778.24   199.3 2774.72
   211.3 2772.66   223.3 2772.84   227.3 2772.09   253.62763.043   259.3 2761.97
  264.832763.042   267.3 2764.23   271.3 2764.59   299.3  2764.8   311.3 2767.17
   315.3 2769.39   327.3 2779.91   334.1 2783.73   339.3 2785.43   355.3 2787.99
   359.3 2789.45   371.3 2796.97   404.4 2813.61   427.3 2823.03     450 2831.08
#Mann= 5, -1 ,  0
       0    0.06       0      40    0.07       0     140     0.1       0
   253.6   0.045       0  264.83     0.1       0
Bank Sta=253.6,264.83
XS Rating Curve= 0 ,0
Exp/Cntr(USF)=0,0
Exp/Cntr=0.3,0.1

Type RM Length L Ch R = 1 ,6249    ,219.6,216.9,219.2
XS GIS Cut Line= 2
2414739.03995252717251.5996849542415188.46214739717274.396411868
#Sta/Elev= 30
       0 2788.62    21.2 2787.72    65.2 2783.62    73.2 2783.87   105.3  2780.9
   125.3 2779.93   173.4 2774.84   181.4 2771.94   185.4 2769.24   193.4 2762.47
   205.4 2750.68  209.392748.166   221.4 2747.39  234.992748.164   241.4 2749.45
   257.5 2755.75   265.5 2757.19   281.5 2755.49   293.5 2756.46   317.5 2755.51
   333.6 2756.31   345.6  2758.8   357.6 2764.37   369.6 2767.32   393.6 2779.03
   400.4 2783.61   413.7 2794.45   433.3 2807.61   440.9 2811.95     450    2816
#Mann= 4, -1 ,  0
       0    0.06       0      80     0.1       0  209.39   0.045       0
  234.99     0.1       0
Bank Sta=209.39,234.99
XS Rating Curve= 0 ,0
Exp/Cntr(USF)=0,0
Exp/Cntr=0.3,0.1

Type RM Length L Ch R = 1 ,6032    ,270.2,270.8,268.4
XS GIS Cut Line= 3
2414734.57844234717433.2184779012415087.22615463717468.768146331
2415167.22637965717461.291264566
#Sta/Elev= 30
       0  2769.2    33.8 2766.49    49.8 2768.31    61.9 2768.08      82 2769.85
   126.2 2766.62   134.3 2764.94   162.4 2754.86   174.5    2752   198.6 2753.91
   226.7 2752.77   242.8 2747.32   258.9 2745.06   266.9 2741.15     279 2739.25
  289.53 2736.13   295.1 2735.55   311.9 2736.13   319.2 2739.78   327.2 2747.03
   335.3 2752.02   347.3 2754.27   363.4 2755.17   375.5 2760.12   403.6 2777.52
   407.6 2780.93   415.6 2791.68   419.7 2794.96   427.7 2799.79   434.8 2802.39
#Mann= 3, -1 ,  0
       0     0.1       0  289.53   0.045       0   311.9     0.1       0
Bank Sta=289.53,311.9
XS Rating Curve= 0 ,0
Exp/Cntr(USF)=0,0
Exp/Cntr=0.3,0.1

Type RM Length L Ch R = 1 ,5761    ,140.6,143.5,145.9
XS GIS Cut Line= 2
2414729.66435046717707.5117525382415179.05952178717730.835131376
#Sta/Elev= 30
       0  2747.5    14.5    2745    42.6 2742.01    62.6 2741.67    78.6 2743.29
   114.7 2742.23   126.7 2741.02   150.7  2740.3   170.7 2736.49   186.8 2736.37
   238.8 2733.62   242.8 2733.01   254.9 2727.47   262.9 2725.51   286.9 2728.08
   294.9 2727.45   306.9 2729.57   314.9 2729.29  324.56 2725.57   334.6 2724.94
  343.712725.585     347 2726.73     355 2731.45     363  2738.2     391 2764.56
     395  2768.9   403.1 2779.89   407.6 2783.84     419 2790.01     450 2801.43
#Mann= 4, -1 ,  0
       0    0.06       0      90     0.1       0  324.56   0.045       0
  343.71     0.1       0
Bank Sta=324.56,343.71
XS Rating Curve= 0 ,0
Exp/Cntr(USF)=0,0
Exp/Cntr=0.3,0.1

Type RM Length L Ch R = 1 ,5617    ,184.9,187.2,183.7
XS GIS Cut Line= 2
2414703.77109965717749.5757263992415146.14504268717900.861324933
#Sta/Elev= 30
       0 2750.39    21.6 2744.66    34.2 2742.27    42.7 2741.47    51.2 2738.42
    55.4 2738.02    91.4 2737.29   118.8  2738.7   134.8 2738.64     178 2737.14
   203.3 2734.13   223.7 2735.42   232.9 2734.34   245.6 2734.63   262.5  2732.4
   279.4 2732.55   287.9 2731.85   296.8 2730.73     309 2726.25  334.382719.425
   351.3 2718.71  356.512719.425   359.8  2720.5     364 2724.01   372.4  2735.5
   389.4 2754.36   403.2 2767.01   440.1 2793.06   453.6 2800.58   467.5 2806.27
#Mann= 4, -1 ,  0
       0    0.06       0      20     0.1       0  334.38   0.045       0
  356.51     0.1       0
Bank Sta=334.38,356.51
XS Rating Curve= 0 ,0
Exp/Cntr(USF)=0,0
Exp/Cntr=0.3,0.1

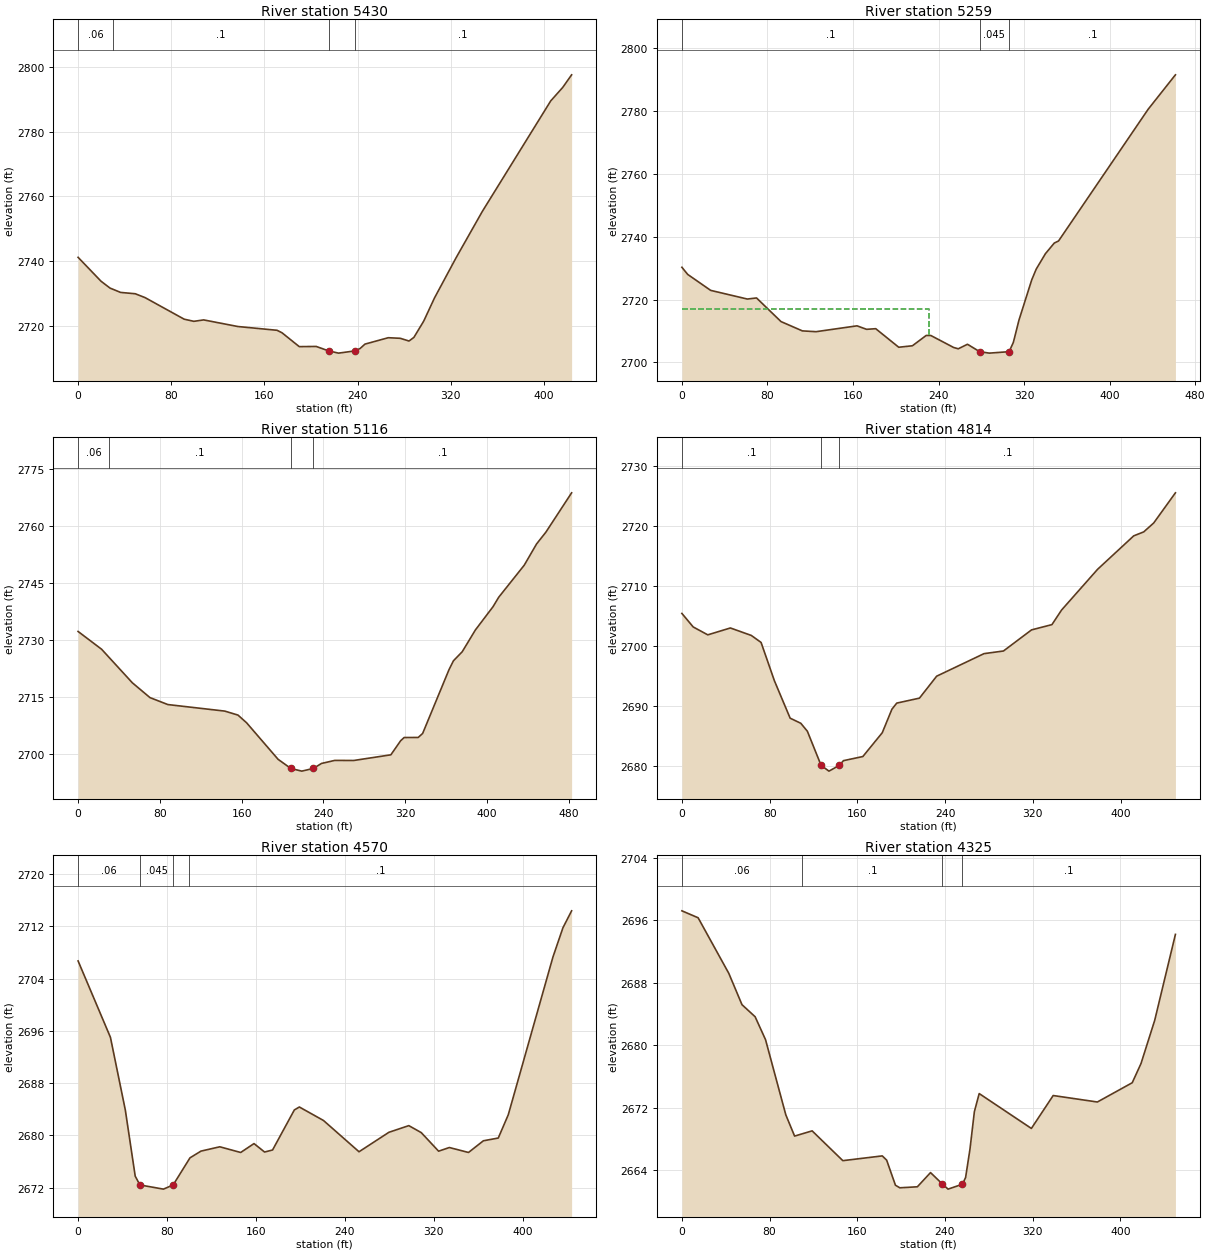
Type RM Length L Ch R = 1 ,5430    ,165.7,171.1,169.5
XS GIS Cut Line= 2
2414693.38362063717925.5636668892415097.22159299718053.649650042
#Sta/Elev= 30
       0 2741.24    19.7 2733.87    27.4 2731.76    36.5 2730.42    49.1 2730.01
    57.5 2728.82    91.1 2722.17    99.4 2721.51   107.8 2721.95   137.2 2719.91
   170.8 2718.75     175    2718   189.9 2713.71   204.4 2713.77  215.212712.387
   223.6 2711.71  237.532712.387   242.1 2713.13   246.3 2714.49   266.3 2716.46
   276.6 2716.28   284.1 2715.44   288.3 2716.56   296.7 2721.56     306 2728.73
   324.4 2741.03     347 2755.36   405.8 2789.47   416.1 2793.62   423.7 2797.49
#Mann= 4, -1 ,  0
       0    0.06       0      30     0.1       0  215.21   0.045       0
  237.53     0.1       0
Bank Sta=215.21,237.53
XS Rating Curve= 0 ,0
Exp/Cntr(USF)=0,0
Exp/Cntr=0.3,0.1

Type RM Length L Ch R = 1 ,5259    ,141.2,143.4,146.3
XS GIS Cut Line= 3
 2414647.1087694718054.3315597962414967.23322133718178.348097438
2415085.43218157718182.150640727
#Sta/Elev= 30
       0 2730.28     5.4 2728.02    26.9 2722.94    61.2 2720.18    69.8 2720.53
    92.7 2713.01   112.7 2710.05   125.5  2709.8   163.8 2711.66   172.7 2710.55
   181.3 2710.75   202.8 2704.85   215.6 2705.32   228.5  2708.6   232.8 2708.59
   254.2 2704.77   258.5 2704.36   267.1  2705.8  278.532703.441   287.5 2702.98
  306.05 2703.44     310 2706.38   315.3 2713.52   327.2 2726.28   331.4  2729.7
     340  2734.6   348.3 2737.99   352.3 2738.66   436.1 2780.54   461.6 2791.49
#Mann= 3, -1 ,  0
       0     0.1       0  278.53   0.045       0  306.05     0.1       0
#XS Ineff= 2 , 0
          230.89 2716.94
Permanent Ineff=
       F       F
Bank Sta=278.53,306.05
XS Rating Curve= 0 ,0
Exp/Cntr(USF)=0,0
Exp/Cntr=0.3,0.1

Type RM Length L Ch R = 1 ,5116    ,300.2,302.1,302.1
XS GIS Cut Line= 2
2414590.77733331718136.696632221 2415039.6814509718314.223756193
#Sta/Elev= 30
       0 2732.18      23  2727.5    53.1 2718.67    70.3 2714.78    87.8 2712.95
   143.5 2711.23   156.4 2710.18   164.8 2708.16   195.6 2698.55  208.152696.136
   218.8 2695.44  229.962696.136   238.1 2697.46     251 2698.26   269.6 2698.24
   305.9 2699.73   315.5 2703.44   318.9 2704.28   332.7  2704.3     337 2705.35
   362.8 2722.14   367.1 2724.46   375.7 2726.84   388.6 2732.58   405.8 2738.68
   411.4 2741.18   436.4 2749.63   448.4 2755.19   457.5 2758.29   482.7 2768.65
#Mann= 4, -1 ,  0
       0    0.06       0      30     0.1       0  208.15   0.045       0
  229.96     0.1       0
Bank Sta=208.15,229.96
XS Rating Curve= 0 ,0
Exp/Cntr(USF)=0,0
Exp/Cntr=0.3,0.1

Type RM Length L Ch R = 1 ,4814    ,245.6,244.1,241.7
XS GIS Cut Line= 2
2414522.82221596718418.3813550692414930.11471053718609.726132542
#Sta/Elev= 30
       0 2705.42    10.3 2703.16    23.6 2701.84    44.2 2702.99    63.3 2701.74
    72.2 2700.57    84.3 2694.19    98.7 2687.91   108.4 2687.06   114.4 2685.73
  126.932680.019   134.1 2679.06  143.51 2680.02   147.3 2680.81     165  2681.5
   182.7 2685.48   191.5 2689.41   195.9 2690.43   216.6 2691.26   232.3 2694.93
   275.5  2698.7   293.2 2699.14   318.8 2702.67   337.4 2703.55   346.2 2705.99
     379 2712.79     412 2718.39   421.1 2719.05   430.2 2720.54     450 2725.58
#Mann= 3, -1 ,  0
       0     0.1       0  126.93   0.045       0  143.51     0.1       0
Bank Sta=126.93,143.51
XS Rating Curve= 0 ,0
Exp/Cntr(USF)=0,0
Exp/Cntr=0.3,0.1

Type RM Length L Ch R = 1 ,4570    ,252.6,244.9,233.3
XS GIS Cut Line= 2
2414430.19991005718626.7396529492414827.19724708718825.862491388
#Sta/Elev= 30
       0  2706.7    29.1 2695.01    42.5 2683.88    51.4 2673.76   55.62 2672.41
    76.8 2671.77   85.532672.409   100.7 2676.56   110.6 2677.59   127.5 2678.25
   146.3 2677.38   158.3 2678.74   167.8 2677.45     175 2677.76   194.6 2683.89
   199.1 2684.34   220.8 2682.28   252.8 2677.49   279.7 2680.47   297.6 2681.49
   308.8 2680.42   324.4 2677.58   334.1 2678.14   351.3 2677.38   364.7 2679.17
   378.1 2679.59   387.1 2683.15   427.3  2707.3   436.3 2711.78   444.1 2714.37
#Mann= 4, -1 ,  0
       0    0.06       0   55.62   0.045       0   85.53    0.06       0
     100     0.1       0
Bank Sta=55.62,85.53
XS Rating Curve= 0 ,0
Exp/Cntr(USF)=0,0
Exp/Cntr=0.3,0.1

Type RM Length L Ch R = 1 ,4325    ,198.9,200.1,199.5
XS GIS Cut Line= 2
2414317.41574316718867.1185460662414767.58489053718864.583304276
#Sta/Elev= 30
       0 2697.24    14.8 2696.35    42.8 2689.22    54.8 2685.21    66.8 2683.66
    76.3 2680.72    94.8 2671.08   102.8 2668.36   118.8 2669.03   146.8 2665.21
   182.8 2665.82   186.8 2665.27   194.8 2662.06   198.8 2661.73   214.8 2661.86
   226.8 2663.68  237.72  2662.2   242.8 2661.56  255.872662.187   258.8 2663.05
   262.8  2666.7   266.8 2671.49   271.2 2673.81   318.8 2669.34   338.7 2673.56
     379 2672.73   410.8  2675.2   418.8 2677.66   431.3  2683.2   450.2 2694.22
#Mann= 4, -1 ,  0
       0    0.06       0     110     0.1       0  237.72   0.045       0
  255.87     0.1       0
Bank Sta=237.72,255.87
XS Rating Curve= 0 ,0
Exp/Cntr(USF)=0,0
Exp/Cntr=0.3,0.1

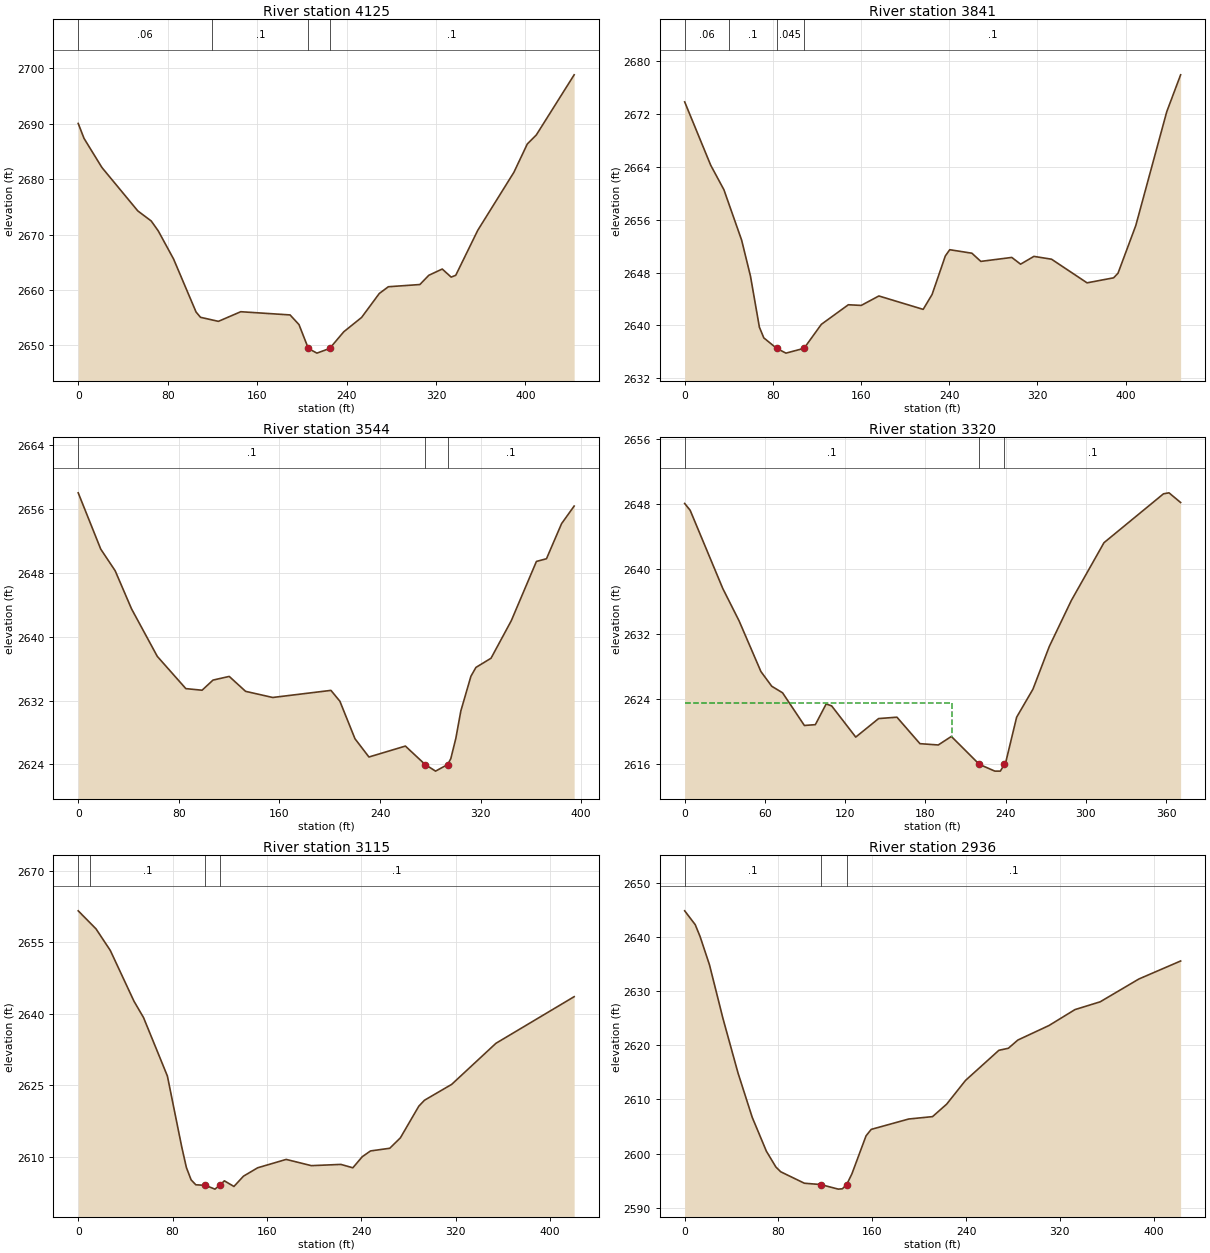
Type RM Length L Ch R = 1 ,4125    ,284.1,283.6,281.6
XS GIS Cut Line= 2
2414298.96111431719043.2012982622414742.03322315719065.810578613
#Sta/Elev= 30
       0 2690.07     5.2 2687.37    21.2 2682.11    53.3 2674.27    65.3 2672.45
    71.6 2670.66    85.3 2665.58   105.4 2656.01   109.4 2655.05   125.4 2654.32
   145.4 2656.06   189.5 2655.48   197.5 2653.73  205.852649.423   213.5 2648.58
  224.932649.423   237.5 2652.43   253.5 2655.03   269.3 2659.35   277.4 2660.57
   305.6 2660.97   313.6 2662.64   325.6 2663.77   333.6 2662.31   337.7 2662.64
   357.4 2670.77   389.7 2681.24   401.7 2686.36   409.7 2687.97   443.6 2698.85
#Mann= 4, -1 ,  0
       0    0.06       0     120     0.1       0  205.85   0.045       0
  224.93     0.1       0
Bank Sta=205.85,224.93
XS Rating Curve= 0 ,0
Exp/Cntr(USF)=0,0
Exp/Cntr=0.3,0.1

Type RM Length L Ch R = 1 ,3841    ,300.9,297.2,291.6
XS GIS Cut Line= 2
2414280.71094529719282.818594198 2414728.7133262719325.172657772
#Sta/Elev= 30
       0 2673.86    23.6 2664.27    35.6 2660.55    51.7  2652.9    59.7 2647.46
    67.8 2639.72    71.8  2638.1   83.392636.522    91.9 2635.79  108.322636.521
     124 2640.15   148.5 2643.12   160.2 2643.02   176.2 2644.45   216.4 2642.42
   224.5 2644.68   236.5 2650.51   240.5 2651.46   260.6 2650.93   268.7 2649.69
   296.8 2650.29   304.8 2649.27   316.9 2650.45   332.9 2650.02   365.1 2646.44
   389.2  2647.2   393.2  2647.9   409.3 2655.11   437.4 2672.36     450 2677.96
#Mann= 4, -1 ,  0
       0    0.06       0      40     0.1       0   83.39   0.045       0
  108.32     0.1       0
Bank Sta=83.39,108.32
XS Rating Curve= 0 ,0
Exp/Cntr(USF)=0,0
Exp/Cntr=0.3,0.1

Type RM Length L Ch R = 1 ,3544    ,222,223.5,225.8
XS GIS Cut Line= 3
2414252.91764659719462.4269361242414413.28174005719527.738009127
2414634.10553427719514.363136352
#Sta/Elev= 30
       0 2658.04    17.9 2650.99    29.4 2648.27    42.4  2643.5    62.9 2637.54
    85.6  2633.5    98.5  2633.3   107.2 2634.57   120.1 2635.03   133.1 2633.16
   154.7 2632.39     201 2633.28   208.1 2631.92   220.1 2627.22   231.2 2624.93
   260.2  2626.3  275.912623.989   284.2 2623.16  293.812623.989   296.3 2624.72
   300.3 2627.26   304.3 2630.71   312.3 2635.05   316.3 2636.16   328.3 2637.31
   344.4 2642.01   364.4 2649.44   372.4 2649.78   384.4 2654.18   394.4 2656.38
#Mann= 3, -1 ,  0
       0     0.1       0  275.91   0.045       0  293.81     0.1       0
Bank Sta=275.91,293.81
XS Rating Curve= 0 ,0
Exp/Cntr(USF)=0,0
Exp/Cntr=0.3,0.1

Type RM Length L Ch R = 1 ,3320    ,206.4,205.3,209.2
XS GIS Cut Line= 2
2414232.17042527719688.0700072182414596.74583942 719755.90505733
#Sta/Elev= 30
       0 2648.07     4.1 2647.23    28.5  2637.6    40.7 2633.61      57 2627.38
    65.1 2625.57    73.2 2624.76    89.5 2620.74    97.7 2620.84   105.8 2623.39
   109.9 2623.15   127.9 2619.31     145 2621.59   158.7 2621.76   175.9  2618.5
   189.6 2618.34   199.4 2619.39  220.282615.959   231.9 2615.12     236 2615.12
  239.072615.959   240.1 2616.24   248.2 2621.76   260.4 2625.21   272.6 2630.46
   289.1 2636.13   313.5 2643.24     358 2649.26   362.1 2649.38   370.8 2648.19
#Mann= 3, -1 ,  0
       0     0.1       0  220.28   0.045       0  239.07     0.1       0
#XS Ineff= 2 , 0
          199.66 2623.53
Permanent Ineff=
       F       F
Bank Sta=220.28,239.07
XS Rating Curve= 0 ,0
Exp/Cntr(USF)=0,0
Exp/Cntr=0.3,0.1

Type RM Length L Ch R = 1 ,3115    ,181.1,179.2,180.3
XS GIS Cut Line= 3
2414221.19189233719879.6150654782414507.72614397  719915.3021306
2414617.72970164719843.013859481
#Sta/Elev= 30
       0 2661.59    15.1  2657.8    27.2 2653.27    47.3  2642.6    55.4 2639.16
    75.6  2626.9    87.7 2612.08    91.7 2607.69    95.7  2605.1    99.7 2604.06
   107.8 2603.95   115.9 2603.15   119.9 2603.95   123.9 2604.89     132 2603.71
   140.1 2605.87   152.1 2607.63   176.3 2609.39   197.6 2608.08   222.7 2608.34
   232.8 2607.63   240.8 2609.96   247.8 2611.17   264.1 2611.73   273.1 2613.92
   288.7 2620.56   293.5 2621.81   316.6 2625.15   354.1 2633.77   420.4 2643.56
#Mann= 4, -1 ,  0
       0    0.06       0      10     0.1       0   107.8   0.045       0
   119.9     0.1       0
Bank Sta=107.8,119.9
XS Rating Curve= 0 ,0
Exp/Cntr(USF)=0,0
Exp/Cntr=0.3,0.1

Type RM Length L Ch R = 1 ,2936    ,334.4,335,335.8
XS GIS Cut Line= 3
2414267.24180804720077.5248758482414549.52606608720034.371101727
2414673.42952382719974.975812523
#Sta/Elev= 30
       0 2644.89       9 2642.33    13.1 2640.16    21.2 2634.87    32.7 2624.94
    45.5 2614.89    57.6  2606.7    69.7 2600.42    77.8  2597.5    81.9 2596.62
   102.1  2594.5  116.052594.259     131 2593.41   134.5 2593.47  138.172594.258
   142.6 2596.22   154.7 2603.27   159.1 2604.46   191.1 2606.38   211.4 2606.82
   223.5 2609.14   239.5 2613.51     268 2619.09   276.1 2619.47   284.2 2620.99
   310.7 2623.67   332.9 2626.62   354.4 2628.06   387.4 2632.28     423 2635.61
#Mann= 3, -1 ,  0
       0     0.1       0  116.05   0.045       0  138.17     0.1       0
Bank Sta=116.05,138.17
XS Rating Curve= 0 ,0
Exp/Cntr(USF)=0,0
Exp/Cntr=0.3,0.1

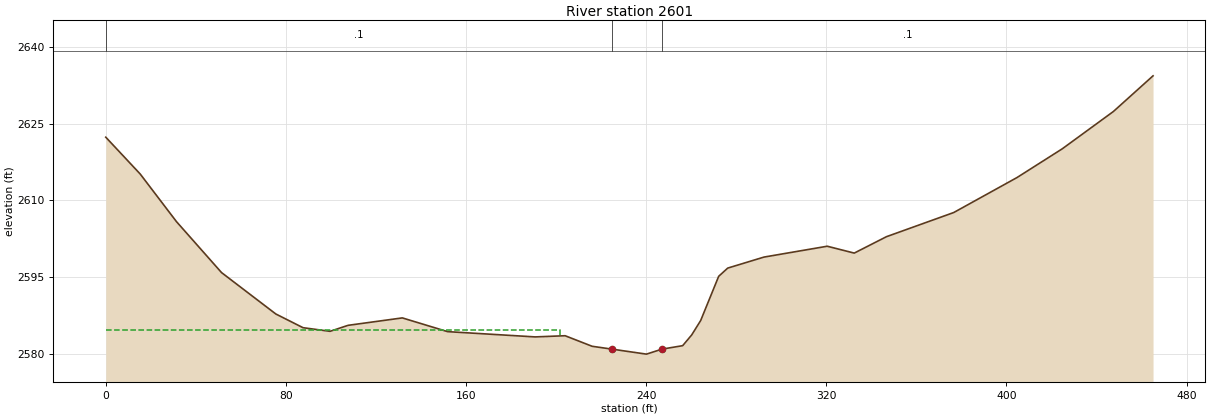
Type RM Length L Ch R = 1 ,2601    ,204.4,203.8,204.3
XS GIS Cut Line= 2
2414352.91000277720323.9522960822414816.37644511720285.015369333
#Sta/Elev= 30
       0 2622.35    15.3 2615.16    31.4 2605.87    51.4 2595.93    75.5 2587.85
    87.6 2585.17    99.6 2584.46   107.6 2585.63   131.7 2587.08   151.8  2584.4
   190.7 2583.37     204  2583.6     216 2581.54  224.652580.994   240.1 2580.01
  247.122580.994   256.2 2581.66   260.2 2583.75   264.2 2586.57   272.2  2595.2
   276.2  2596.8   292.3 2598.95   320.4 2601.07   332.4 2599.73   346.7 2602.93
   376.6 2607.65   404.7 2614.48   424.8 2620.09   447.5 2627.37   465.1 2634.33
#Mann= 3, -1 ,  0
       0     0.1       0  224.65   0.045       0  247.12     0.1       0
#XS Ineff= 2 , 0
           201.9 2584.79
Permanent Ineff=
       F       F
Bank Sta=224.65,247.12
XS Rating Curve= 0 ,0
Exp/Cntr(USF)=0,0
Exp/Cntr=0.3,0.1