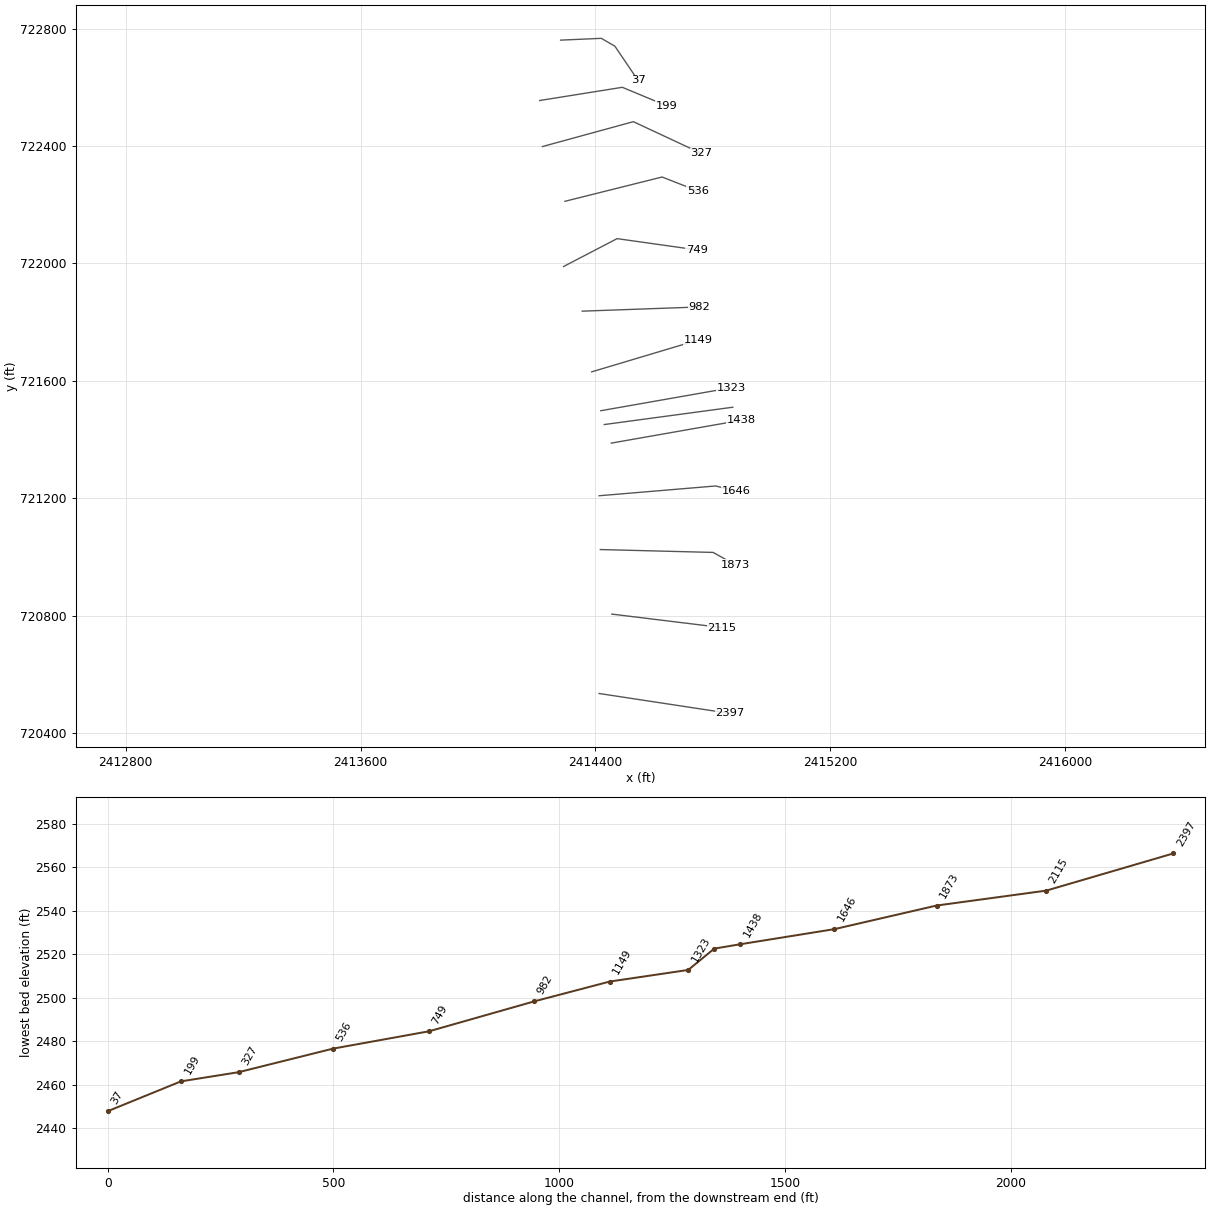
HEC-RAS study FLATROCKRN.prj: FLATROCKRN

--- FLATROCKRN.g01 (geometry) --- (continued)

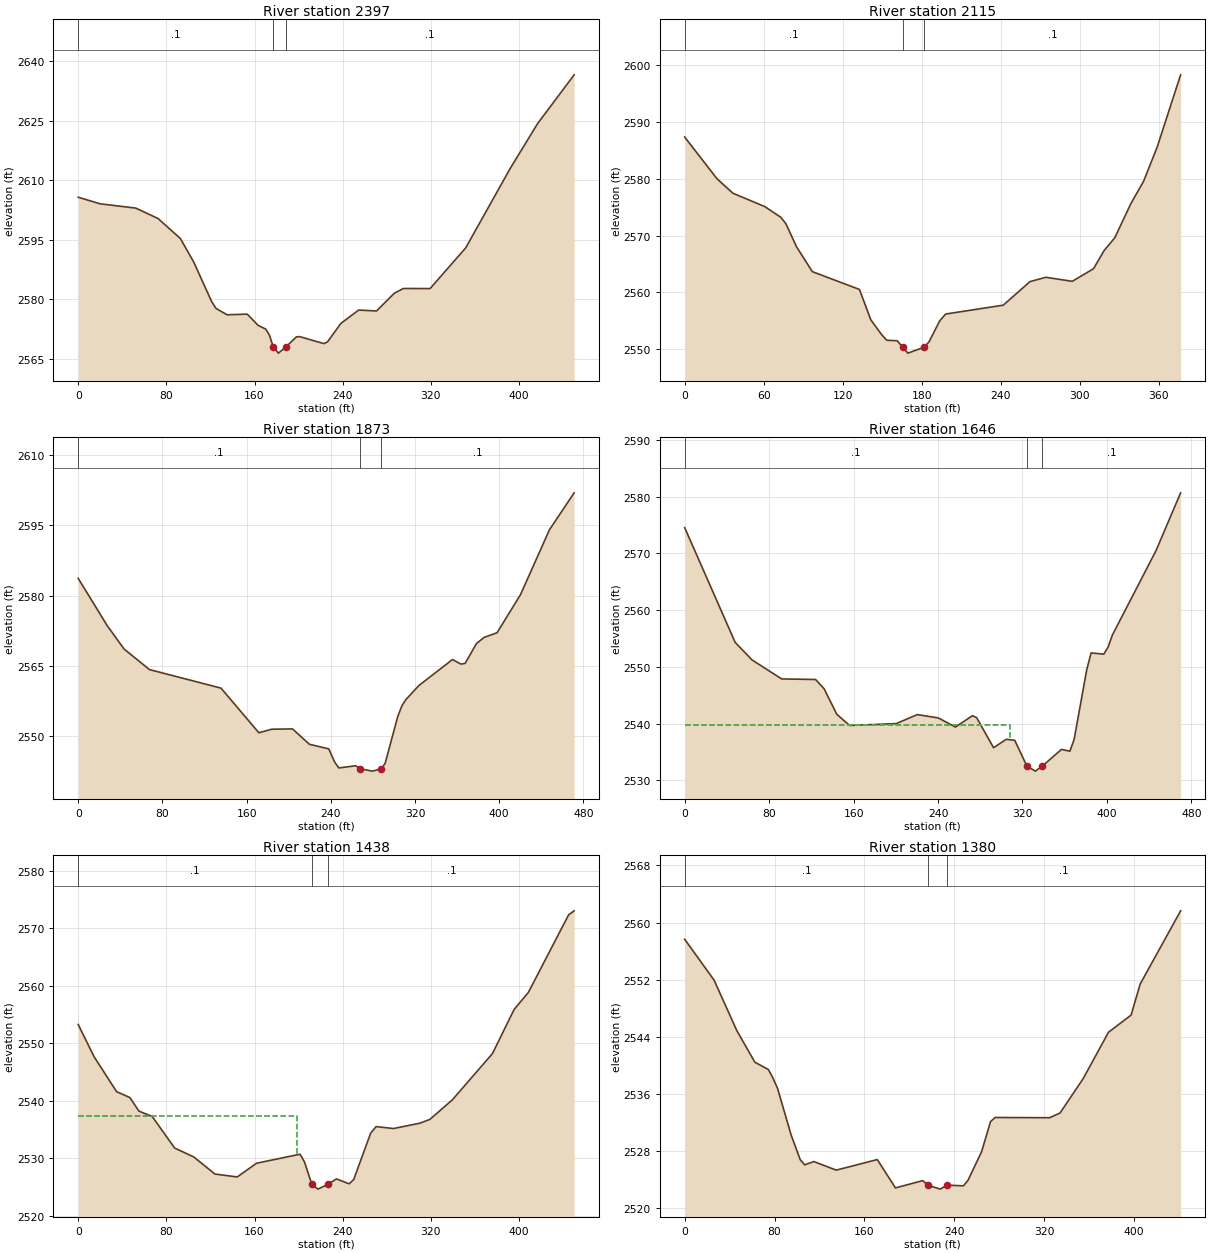
Type RM Length L Ch R = 1 ,2397    ,281.1,281.7,281.5
XS GIS Cut Line= 2
2414412.54675044720535.3951779752414857.42814564720467.715460178
#Sta/Elev= 30
       0 2605.77    19.9 2604.11    52.2 2603.03    72.5 2600.39    92.7 2595.36
   104.8 2589.44     121  2579.5   125.1 2577.72   135.1 2576.13   153.4 2576.29
   163.2 2573.47   170.2 2572.51   173.6 2570.94  177.052567.932   181.7 2566.46
  188.112567.935   197.9 2570.54   200.9 2570.63   222.9 2568.86   226.2 2569.29
   238.3 2573.95   254.5 2577.32   270.7 2577.09   286.9 2581.58     295 2582.75
   319.3 2582.74   351.6    2593   392.1 2613.08   416.8 2624.32     450 2636.63
#Mann= 3, -1 ,  0
       0     0.1       0  177.05   0.045       0  188.11     0.1       0
Bank Sta=177.05,188.11
XS Rating Curve= 0 ,0
Exp/Cntr(USF)=0,0
Exp/Cntr=0.3,0.1

Type RM Length L Ch R = 1 ,2115    ,242.6,242.6,245.2
XS GIS Cut Line= 2
 2414455.8480896720805.8204962082414829.89172952720760.011514465
#Sta/Elev= 30
       0 2587.32    24.5    2580    36.6 2577.45    60.8  2575.1    72.9 2573.24
    76.9  2572.1      85 2568.02      97 2563.66   132.8 2560.53   141.4 2555.21
   149.4 2552.66   153.5 2551.61   161.5 2551.51  165.652550.387   169.6 2549.34
     1822550.388   185.7 2551.34   193.8 2555.03   198.3 2556.21   242.1 2557.77
   262.3  2561.9   274.4 2562.67   294.5 2561.96   310.6 2564.17   318.7 2567.37
   326.8 2569.62   338.8 2575.52   348.7 2579.56     359 2585.55   376.8 2598.25
#Mann= 3, -1 ,  0
       0     0.1       0  165.65   0.045       0     182     0.1       0
Bank Sta=165.65,182
XS Rating Curve= 0 ,0
Exp/Cntr(USF)=0,0
Exp/Cntr=0.3,0.1

Type RM Length L Ch R = 1 ,1873    ,224.5,226.4,224.7
XS GIS Cut Line= 3
 2414416.5450772 721025.609761162414800.80302666721015.819749709
 2414876.6756154720973.396366754
#Sta/Elev= 30
       0  2583.7    27.6 2573.57    43.6 2568.59    67.7  2564.2   135.7 2560.23
   171.7 2550.69   183.9 2551.45   203.7 2551.51   219.7 2548.23   238.1 2547.25
   243.7 2544.43   247.7 2543.17   263.7 2543.64   267.7 2542.99   279.7 2542.49
  288.19    2543   291.7 2544.17   303.7  2554.2   307.7 2556.51   311.7 2557.85
   323.7 2560.78   355.7 2566.35   363.7 2565.37   367.7 2565.52   378.5 2569.77
   385.9  2571.1     398 2572.06   420.3 2580.21   447.8 2594.07   471.3 2601.98
#Mann= 3, -1 ,  0
       0     0.1       0   267.7   0.045       0  288.19     0.1       0
Bank Sta=267.7,288.19
XS Rating Curve= 0 ,0
Exp/Cntr(USF)=0,0
Exp/Cntr=0.3,0.1

Type RM Length L Ch R = 1 ,1646    ,207.6,208.8,208.8
XS GIS Cut Line= 3
2414412.56964451721208.8339242942414809.26706782721242.111545658
2414878.78595351721224.620630372
#Sta/Elev= 30
       0 2574.55    47.8 2554.33    63.8 2551.23    91.9 2547.88     124 2547.78
   132.1 2546.14   144.1 2541.65   156.2 2539.68   200.3    2540   220.4 2541.59
   240.2 2541.01   256.5  2539.4   272.6  2541.4   276.6 2541.05   292.6 2535.76
   304.7 2537.24   312.7 2537.06  324.122532.532   332.2 2531.63   338.9 2532.53
   356.9 2535.46   364.9 2535.14   368.9  2537.2   380.9 2549.52     385 2552.46
     397 2552.25   401.1 2553.49   405.2 2555.63   446.5 2570.49   469.8 2580.68
#Mann= 3, -1 ,  0
       0     0.1       0  324.12   0.045       0   338.9     0.1       0
#XS Ineff= 2 , 0
          308.13 2539.81
Permanent Ineff=
       F       F
Bank Sta=324.12,338.9
XS Rating Curve= 0 ,0
Exp/Cntr(USF)=0,0
Exp/Cntr=0.3,0.1

Type RM Length L Ch R = 1 ,1438    ,58.3,57.2,57.4
XS GIS Cut Line= 2
2414453.94889252721388.0715104722414897.14430135721466.031946529
#Sta/Elev= 30
       0  2553.3    14.4  2547.7    34.8 2541.63    46.9 2540.59    55.1 2538.24
    67.2 2537.29    87.5 2531.82   104.9 2530.26   124.1 2527.29   144.3 2526.79
   161.8 2529.17   201.3 2530.74   205.3  2529.4  211.912525.557   217.5 2524.67
   227.12525.555   234.3 2526.45   245.9 2525.59     250 2526.35   265.4 2534.42
   270.3 2535.54   286.1 2535.21   310.3 2536.15   319.1  2536.8   339.4 2540.18
   375.9 2548.25   395.6 2555.94   408.4 2558.86     445 2572.38     450 2573.07
#Mann= 3, -1 ,  0
       0     0.1       0  211.91   0.045       0   227.1     0.1       0
#XS Ineff= 2 , 0
          198.37 2537.36
Permanent Ineff=
       F       F
Bank Sta=211.91,227.1
XS Rating Curve= 0 ,0
Exp/Cntr(USF)=0,0
Exp/Cntr=0.3,0.1

Type RM Length L Ch R = 1 ,1380    ,57.5,57.7,59
XS GIS Cut Line= 2
2414430.19565466721451.324147531 2414867.8079834721510.286650772
#Sta/Elev= 30
       0 2557.66    26.2 2551.93    46.4 2544.88    62.5 2540.44    74.6 2539.41
    78.1 2538.39    82.7 2536.78    94.8 2530.25   102.9 2526.79   106.9 2526.07
     115 2526.53     135 2525.33   171.5 2526.81   187.7 2522.84   211.9 2523.86
   216.8 2523.22   227.5 2522.67  233.63 2523.23   248.2 2523.13   252.2 2523.88
   264.3 2527.88   272.4 2532.14   276.5  2532.7   324.9 2532.67   334.2 2533.32
   354.7 2538.11   377.4 2544.64   397.5 2547.04   405.6 2551.39   441.6 2561.64
#Mann= 3, -1 ,  0
       0     0.1       0   216.8   0.045       0  233.63     0.1       0
Bank Sta=216.8,233.63
XS Rating Curve= 0 ,0
Exp/Cntr(USF)=0,0
Exp/Cntr=0.3,0.1

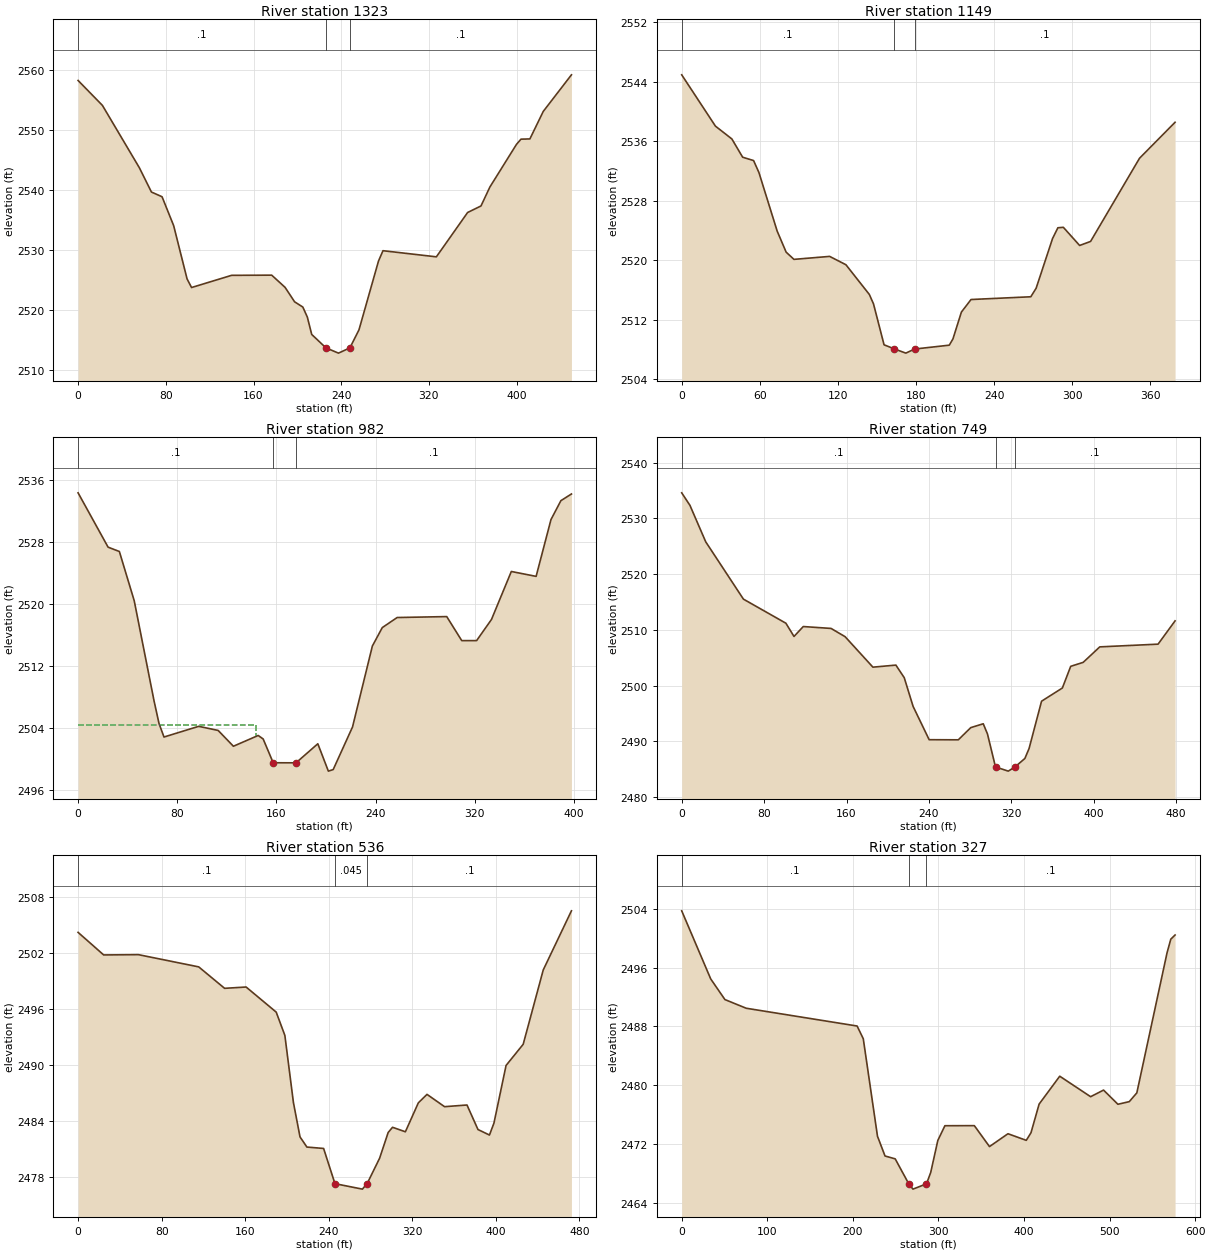
Type RM Length L Ch R = 1 ,1323    ,173.3,173.6,177.9
XS GIS Cut Line= 2
 2414418.2744205721498.3921708642414861.46982933721576.352606921
#Sta/Elev= 30
       0 2558.25    22.2  2554.1    55.9 2543.72    66.9 2539.68    76.6 2538.89
    87.2 2534.07    99.4 2525.22   103.5 2523.78     140 2525.81   176.6 2525.84
   188.8 2523.81   197.5  2521.4     205 2520.53   209.1 2518.86   213.1 2515.97
  226.122513.731   237.5 2512.86  247.912513.732   256.2 2516.73     274 2528.18
   278.1 2529.91   326.8 2528.89   355.3 2536.27   367.5 2537.36   375.6 2540.51
   399.9 2547.62     404 2548.48   412.1 2548.52   424.3  2553.1     450 2559.19
#Mann= 3, -1 ,  0
       0     0.1       0  226.12   0.045       0  247.91     0.1       0
Bank Sta=226.12,247.91
XS Rating Curve= 0 ,0
Exp/Cntr(USF)=0,0
Exp/Cntr=0.3,0.1

Type RM Length L Ch R = 1 ,1149    ,170.1,167.5,165.8
XS GIS Cut Line= 2
2414387.32789198721630.7562814332414750.37414996721739.262241684
#Sta/Elev= 30
       0 2544.96    25.9 2538.06    38.5 2536.34    46.8 2533.88    55.2 2533.43
    59.3 2531.82    73.3 2523.95    80.2 2521.11    86.2 2520.14   113.6 2520.54
   126.1 2519.42   144.1 2515.42   147.3 2514.15   155.4 2508.65   163.3  2508.1
   172.1 2507.53  178.91 2508.08   205.5  2508.6   208.3 2509.44   214.8 2513.05
   222.2 2514.74   268.1 2515.11   272.2 2516.26   284.8 2522.94   288.9 2524.39
   293.1 2524.45   305.6 2522.01     314 2522.55   351.6 2533.74   378.9 2538.58
#Mann= 3, -1 ,  0
       0     0.1       0   163.3   0.045       0  178.91     0.1       0
Bank Sta=163.3,178.91
XS Rating Curve= 0 ,0
Exp/Cntr(USF)=0,0
Exp/Cntr=0.3,0.1

Type RM Length L Ch R = 1 ,982     ,235.5,232.8,232.5
XS GIS Cut Line= 2
 2414354.9218221 721837.430005812414752.67205309721851.653978796
#Sta/Elev= 30
       0 2534.31    24.2  2527.3    33.3 2526.74    45.3 2520.38    61.3 2507.45
    65.3 2504.54    69.3  2502.8    97.3 2504.18     113 2503.65   125.3 2501.61
   145.3    2503   149.3 2502.55   157.4 2499.48   175.8 2499.47   193.4 2501.93
   201.9  2498.4   205.8  2498.6   221.4  2504.1   237.4 2514.54   245.4 2516.92
   257.4 2518.22   297.4 2518.34   309.5 2515.24   321.5 2515.24   333.5 2517.97
   349.5 2524.16   369.5 2523.53   381.5 2530.86   389.5  2533.3     398 2534.16
#Mann= 3, -1 ,  0
       0     0.1       0   157.4   0.045       0   175.8     0.1       0
#XS Ineff= 2 , 0
          143.41 2504.32
Permanent Ineff=
       F       F
Bank Sta=157.4,175.8
XS Rating Curve= 0 ,0
Exp/Cntr(USF)=0,0
Exp/Cntr=0.3,0.1

Type RM Length L Ch R = 1 ,749     ,206.8,212.4,214.5
XS GIS Cut Line= 3
2414291.53299296721989.4891796092414473.75920995722084.409178458
2414744.51046081722046.218454948
#Sta/Elev= 30
       0  2534.6       8 2532.35    23.3 2525.81    59.9 2515.52   101.1  2511.2
     109 2508.82     118  2510.6     145 2510.26   158.6 2508.78   185.6 2503.31
   207.9 2503.68     216 2501.42   224.6 2496.27   240.2 2490.29   268.5 2490.27
   280.6 2492.46   292.7 2493.15   296.8 2491.32  304.592485.397     317 2484.65
  323.492485.399   333.1 2486.92   337.2 2488.72   349.3  2497.2   369.5 2499.57
   377.6 2503.46   389.7 2504.17   405.8 2506.95   462.4 2507.44   478.9 2511.62
#Mann= 3, -1 ,  0
       0     0.1       0  304.59   0.045       0  323.49     0.1       0
Bank Sta=304.59,323.49
XS Rating Curve= 0 ,0
Exp/Cntr(USF)=0,0
Exp/Cntr=0.3,0.1

Type RM Length L Ch R = 1 ,536     ,208.6,209.3,209.8
XS GIS Cut Line= 3
2414296.10543265722211.5127561422414626.90925011722294.257831634
2414749.26892227722246.399387438
#Sta/Elev= 30
       0 2504.21    24.5 2501.79    57.8 2501.82   115.5 2500.51   140.3 2498.21
   160.9 2498.35   189.7 2495.66     198 2493.16   206.2 2485.96   212.5 2482.28
   219.1 2481.19   235.1 2481.04  245.962477.266   272.2 2476.68  276.762477.266
   288.7 2479.99   296.9 2482.75   301.1 2483.31   313.4 2482.83   325.8 2485.93
   334.1 2486.84   350.9 2485.52   372.4  2485.7   382.9 2483.07   393.9 2482.48
   398.2 2483.76   409.8 2489.94   426.2 2492.21   445.4 2500.18   472.4 2506.52
#Mann= 3, -1 ,  0
       0     0.1       0  245.96   0.045       0  276.76     0.1       0
Bank Sta=245.96,276.76
XS Rating Curve= 0 ,0
Exp/Cntr(USF)=0,0
Exp/Cntr=0.3,0.1

Type RM Length L Ch R = 1 ,327     ,129.4,127.8,125.8
XS GIS Cut Line= 3
2414219.49377799722397.9932066772414529.13020889722482.689798813
2414760.71369475722374.544460754
#Sta/Elev= 30
       0 2503.72    33.9 2494.45    50.5 2491.64    75.4 2490.46     205 2488.04
   212.2 2486.31   228.8 2473.04   237.6 2470.35   249.5 2469.96  265.352466.563
   270.3 2465.84  286.082466.562     291  2468.1   299.3 2472.46   307.6 2474.47
     342 2474.48   359.7 2471.63   381.3 2473.38   402.7 2472.48   408.2 2473.51
   417.7 2477.41   441.8 2481.21   477.9 2478.42     493 2479.32   509.8 2477.39
   523.1 2477.75   531.9 2478.94   567.2    2498   571.6 2499.86   576.6 2500.43
#Mann= 3, -1 ,  0
       0     0.1       0  265.35   0.045       0  286.08     0.1       0
Bank Sta=265.35,286.08
XS Rating Curve= 0 ,0
Exp/Cntr(USF)=0,0
Exp/Cntr=0.3,0.1

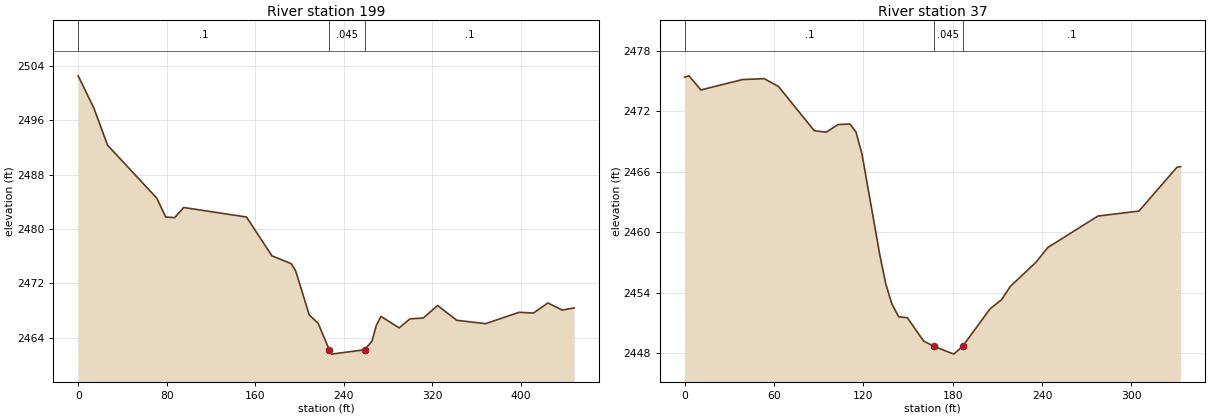
Type RM Length L Ch R = 1 ,199     ,169,162.1,153.4
XS GIS Cut Line= 3
2414210.02575702722554.7747865172414491.57718585722599.737372109
2414642.05354636722536.977514975
#Sta/Elev= 30
       0 2502.55    14.3 2497.75    26.5 2492.35      71 2484.56    79.1 2481.78
    87.2 2481.69    95.3 2483.18   152.1 2481.78   175.1 2476.07   192.6 2474.91
   196.6 2473.82   208.8 2467.39   216.9 2466.14  226.872462.257     229 2461.61
   258.82462.256   265.5 2463.52   269.4 2465.83   273.6 2467.16   290.1 2465.47
   299.8  2466.8   311.8 2466.92   324.8 2468.77   342.1 2466.59   368.1 2466.09
   398.4 2467.76   411.5 2467.66   424.5 2469.14   437.4 2468.09   448.2 2468.41
#Mann= 3, -1 ,  0
       0     0.1       0  226.87   0.045       0   258.8     0.1       0
Bank Sta=226.87,258.8
XS Rating Curve= 0 ,0
Exp/Cntr(USF)=0,0
Exp/Cntr=0.3,0.1

Type RM Length L Ch R = 1 ,37      ,,,
XS GIS Cut Line= 4
 2414281.2686527 722760.381371842414419.99655802722766.508566766
 2414466.2804978722739.7247490332414545.01210442722623.183532427
#Sta/Elev= 30
       0  2475.4     2.9 2475.53    10.9 2474.13    38.9 2475.16    53.4 2475.25
      63 2474.47      87 2470.08      95 2469.93     103 2470.69     111 2470.74
     115 2469.96     119  2467.8     131 2457.76     135 2454.88   139.1 2452.88
   143.7 2451.59   149.5  2451.5   160.5 2449.17  167.29 2448.67   180.7 2447.88
  186.682448.669   205.1 2452.39   212.8 2453.29   218.6  2454.6   235.9 2457.01
   243.7 2458.46   277.5  2461.6     305 2462.09   330.6 2466.45     333 2466.51
#Mann= 3, -1 ,  0
       0     0.1       0  167.29   0.045       0  186.68     0.1       0
Bank Sta=167.29,186.68
XS Rating Curve= 0 ,0
Exp/Cntr(USF)=0,0
Exp/Cntr=0.3,0.1
LCMann Table=0

Chan Stop Cuts=-1
Use User Specified Reach Order=0
Composite Channel Slope=5